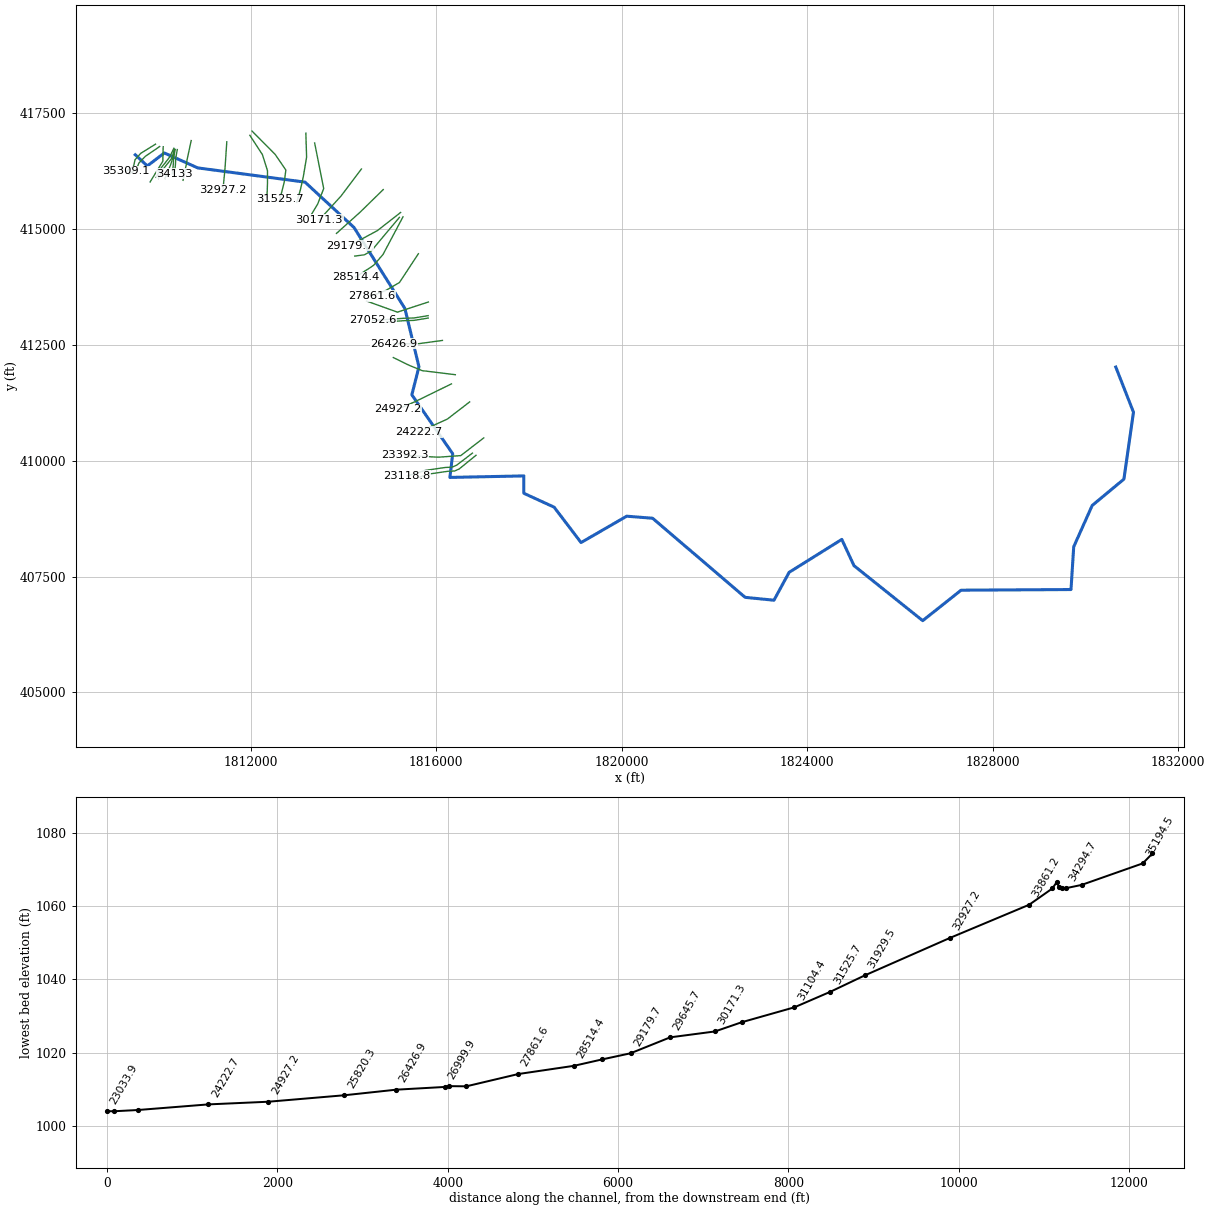
--- DentsRun.prj (project) ---

Proj Title=DentsRun
Current Plan=p01
Default Exp/Contr=0,0
English Units
Geom File=g01
Flow File=f01
Plan File=p01
BEGIN DESCRIPTION:
END DESCRIPTION:
DSS Export Rating Curves= 0
DSS Export Rating Curve Sorted= 0
DSS Export Volume Flow Curves= 0
DXF OffsetX= 0
DXF OffsetY= 0
DXF ScaleX= 0
DXF ScaleY= 0

--- DentsRun.p01 (plan) ---

Plan Title=Floodplain
Program Version=4.00
Geom File=g01
Flow File=f01
K Sum by GR=0
Std Step Tol=0.01
Critical Tol=0.01
Num of Std Step Trials=20
Max Error Tol=0.3
Flow Tol Ratio=0.001
Split Flow NTrial=30
Split Flow Tol=0.02
Split Flow Ratio=0.02
Log Output Level=0
Friction Slope Method=1
Unsteady Friction Slope Method=2
Unsteady Bridges Friction Slope Method=1
Global Log Level=0
CheckData=False
Run HTab=0
Run UNet=0
Run PostProcess=0
UNET Theta=0
UNET Theta Warmup=0
UNET ZTol=0
UNET ZSATol=0
UNET MxIter=0
UNET MaxInSteps=0
UNET DtIC=0
UNET DtMin=0
UNET MaxCRTS=0
UNET WFStab=0
UNET SFStab=0
UNET WFX=0
UNET SFX=0
UNET DSS MLevel=0
UNET DZMax Abort=0
UNET Convert EG Bridges=0
UNET Use Existing IB Tables=0
UNET Froude Limit=0
UNET Froude Power=0
Write IC File=0
Echo Input=False
Echo Output=False
Write Detailed=0

--- DentsRun.f01 (steady flow) ---

Flow Title=NFF Regression Equation
Program Version=4.10
Number of Profiles= 1
Profile Names=P100yr
River Rch & RM=DentsRun,Main            ,35309.1
     596
River Rch & RM=DentsRun,Main            ,33861.2
     889
River Rch & RM=DentsRun,Main            ,31525.7
     936
River Rch & RM=DentsRun,Main            ,30485.5
    1107
River Rch & RM=DentsRun,Main            ,30171.3
    1210
River Rch & RM=DentsRun,Main            ,28514.4
    1272
River Rch & RM=DentsRun,Main            ,27861.6
    1359
River Rch & RM=DentsRun,Main            ,25820.3
    1441
River Rch & RM=DentsRun,Main            ,23118.8
    1503
River Rch & RM=DentsRun,Main            ,22785.2
    1861
River Rch & RM=DentsRun,Main            ,21231
    1878
River Rch & RM=DentsRun,Main            ,20879.4
    2004
River Rch & RM=DentsRun,Main            ,19248.4
    2020
River Rch & RM=DentsRun,Main            ,18953.2
    2226
River Rch & RM=DentsRun,Main            ,13090.2
    2340
River Rch & RM=DentsRun,Main            ,11994.2
    2516
River Rch & RM=DentsRun,Main            ,8658.8
    2599
River Rch & RM=DentsRun,Main            ,3927.2
    2791
River Rch & RM=DentsRun,Main            ,97.7
    2985
Boundary for River Rch & Prof#=DentsRun,Main            , 1
Up Type= 0
Dn Type= 1
Dn Known WS=830.6
DSS Import GetInterval= 0
DSS Import GetPeak= 0
DSS Import FillOption= 0

--- DentsRun.g01 (geometry) ---

Geom Title=USGS 10m DEM
Program Version=4.10

River Reach=DentsRun        ,Main
Reach XY= 30
     1809509.936      416604.867      1809768.79      416364.242
     1810135.978       416643.93     1810857.106      416321.812
     1813170.396      416014.633     1814225.699      415037.001
     1815323.567      413288.738     1815627.351      412028.907
     1815473.566      411425.307     1816355.188      410152.409
     1816294.812      409641.443     1817889.002      409674.113
     1817889.002      409299.448      1818542.02      408999.402
     1819123.032      408235.828     1820107.607      408804.792
     1820665.941      408760.521     1822661.947      407053.056
     1823283.475      406991.424     1823609.864      407592.987
     1824745.975      408303.577     1825009.864      407736.216
      1826490.94      406549.931     1827318.545      407207.744
     1829689.031      407221.633     1829747.538      408144.723
     1830145.975      409036.216     1830830.176      409604.271
     1831036.426      411049.237     1830654.844      412023.764

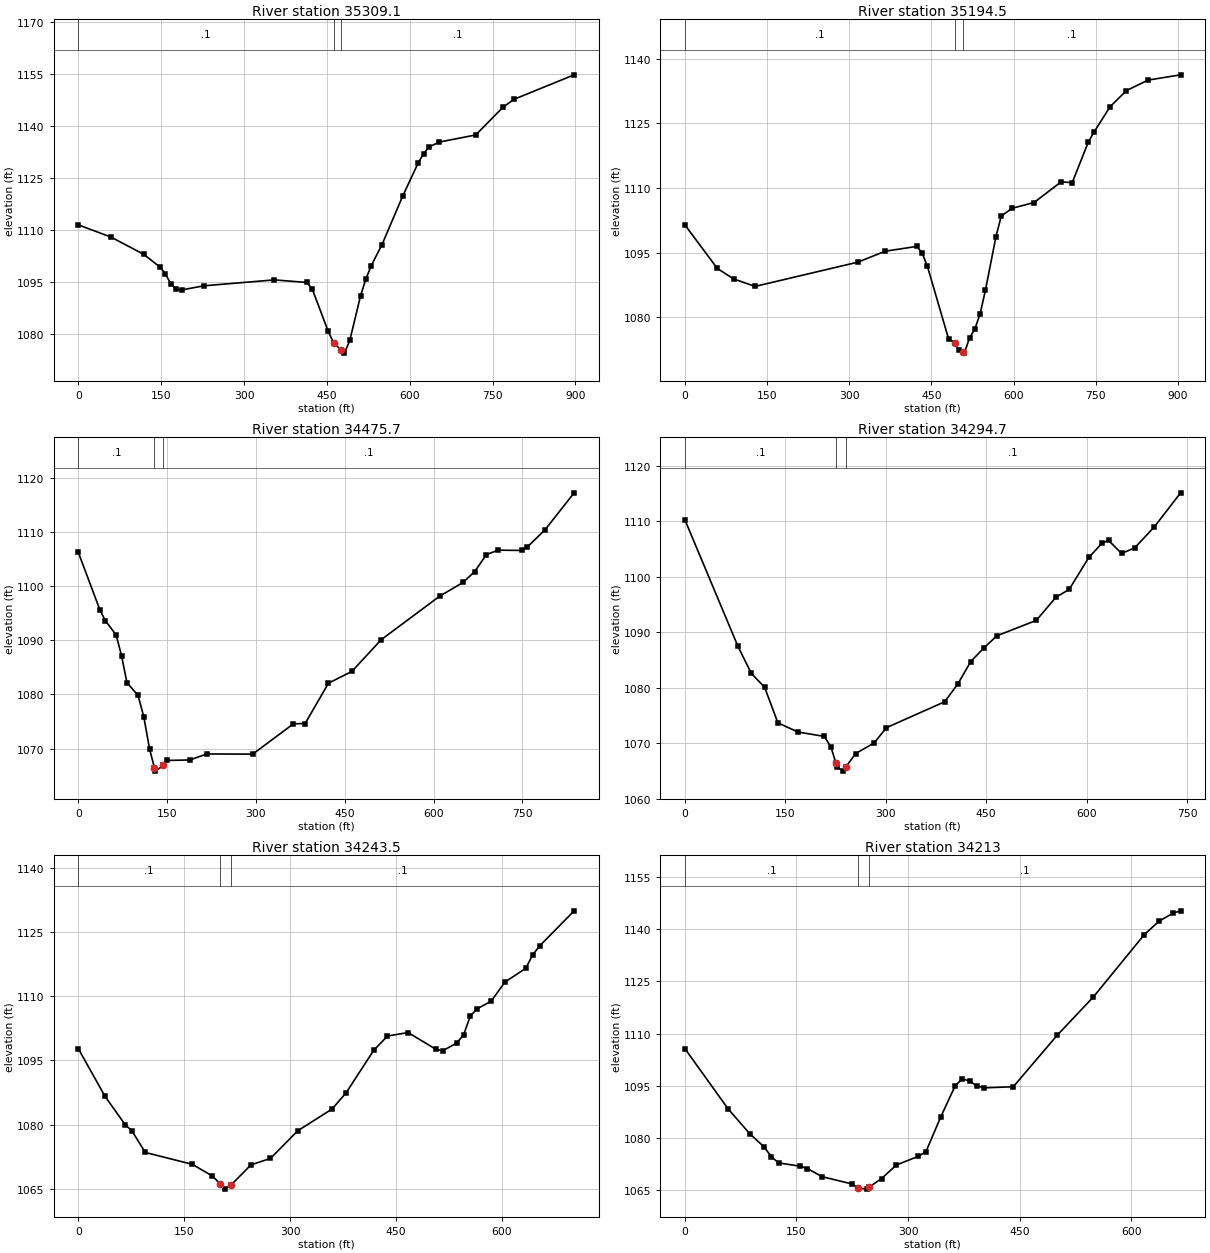
Type RM Length L Ch R = 1 ,35309.1 ,115.3,114.6,114
XS GIS Cut Line= 5
     1809945.613      416833.889     1809627.458       416636.12
     1809504.194      416498.099     1809474.259      416361.233
     1809312.801       416246.65
#Sta/Elev= 30
       0 1111.52    59.2 1107.98   118.3 1103.02   147.9 1099.33   157.7 1097.35
   167.6 1094.46   177.4 1092.94   187.3 1092.72   226.7  1093.9   354.9 1095.62
   413.6 1094.88   423.3 1093.08   452.5 1080.73   462.3 1077.42   475.6  1075.4
   481.8 1074.46   491.5 1078.11     511 1091.01   520.7 1095.89   530.4 1099.76
   549.9 1105.83   587.7 1119.98   615.7 1129.51     625 1132.04   634.4 1133.96
   653.1 1135.42   719.6  1137.5   769.1 1145.54   788.9  1147.8   897.8 1154.87
#Mann= 3 , 0 , 0
       0      .1       0   462.3    .045       0   475.6      .1       0
Bank Sta=462.3,475.6
XS Rating Curve= 0 ,0
Exp/Cntr=0.3,0.1

Type RM Length L Ch R = 1 ,35194.5 ,701.8,718.8,730.8
XS GIS Cut Line= 5
     1810035.457      416783.108     1809725.561      416571.303
     1809586.238      416425.035     1809540.665      416303.941
     1809379.207      416189.358
#Sta/Elev= 30
       0 1101.48    59.3 1091.37    88.9 1088.93   128.4  1087.2   316.1 1092.83
   365.5 1095.35   423.5 1096.47   433.1  1094.9   442.7 1091.84   481.2 1075.09
   492.9 1074.05   500.4 1072.46   507.9 1071.89     510 1071.73   519.6 1075.26
   529.3 1077.35   538.9 1080.87   548.5 1086.28   567.8 1098.76   577.4  1103.5
   597.3 1105.31   637.1 1106.63   686.8 1111.44   706.8 1111.23   736.4 1120.69
   746.4 1122.91     776 1128.84   805.7 1132.57   845.3 1135.02   904.7 1136.24
#Mann= 3 , 0 , 0
       0      .1       0   492.9    .045       0   507.9      .1       0
Bank Sta=492.9,507.9
XS Rating Curve= 0 ,0
Exp/Cntr=0.3,0.1

Type RM Length L Ch R = 1 ,34475.7 ,192.5,181,168.2
XS GIS Cut Line= 4
      1810112.28      416779.202     1810108.374      416688.056
     1810103.165        416465.4     1809829.728      416018.785
#Sta/Elev= 30
       0 1106.23    36.5  1095.6    45.6 1093.64    63.9 1090.98      73 1087.16
    82.1 1082.19   100.9 1079.81   110.6 1075.86   120.3 1069.95   128.6 1066.43
     130 1065.84   143.6 1066.88   149.3 1067.81   188.1  1067.9   217.1 1069.01
   294.6 1068.98   363.4 1074.58   383.1 1074.63   422.6 1082.09   462.2 1084.26
   511.6 1090.11   610.4 1098.15   649.9 1100.69   669.6  1102.7   689.4 1105.83
   709.2 1106.65   748.7  1106.6   758.6 1107.25   788.2 1110.39   837.6 1117.24
#Mann= 3 , 0 , 0
       0      .1       0   128.6    .045       0   143.6      .1       0
Bank Sta=128.6,143.6
XS Rating Curve= 0 ,0
Exp/Cntr=0.3,0.1

Type RM Length L Ch R = 1 ,34294.7 ,53.5,51.3,51.1
XS GIS Cut Line= 5
     1810341.447      416745.348     1810246.395      416548.733
     1810183.895      416469.306     1810062.801       416315.66
     1809959.936      416115.139
#Sta/Elev= 30
       0 1110.28    79.4 1087.43    99.3 1082.57   119.1 1080.09     139 1073.66
   168.8 1072.01   208.5 1071.21   218.4 1069.24   225.5 1066.47   227.6 1065.65
   236.8 1064.96   240.5 1065.71   255.1 1068.13   282.7 1070.03   301.1 1072.79
   387.9 1077.45   407.5 1080.62     427  1084.7   446.6 1087.16   466.2 1089.35
   524.9 1092.12   554.3  1096.3   573.9 1097.69   603.3 1103.46   622.9 1106.01
   632.7 1106.53   652.3 1104.18   671.9 1105.19   701.3 1108.99   740.4  1115.1
#Mann= 3 , 0 , 0
       0      .1       0   225.5    .045       0   240.5      .1       0
Bank Sta=225.5,240.5
XS Rating Curve= 0 ,0
Exp/Cntr=0.3,0.1

Type RM Length L Ch R = 1 ,34243.5 ,22.2,30.4,38.7
XS GIS Cut Line= 5
     1810347.089      416700.382     1810295.006        416527.9
     1810232.506      416448.473     1810111.412      416294.827
     1810008.547      416094.306
#Sta/Elev= 30
       0 1097.77    37.9 1086.57    66.4 1079.96    75.9 1078.54    94.8 1073.47
   161.2 1070.71   189.4    1068   200.6 1066.19   207.7 1064.89   215.6 1065.74
   244.5 1070.57   272.1 1072.07   310.6 1078.52   359.5 1083.66   379.1 1087.41
   418.2 1097.34   437.8 1100.72   467.1 1101.53   506.3 1097.62   516.1 1097.28
   535.7 1099.06   545.5 1100.96   555.3 1105.45   565.1 1107.13   584.7 1108.87
   604.2 1113.36   633.6 1116.55   643.4  1119.7   653.2 1121.79   702.2 1130.02
#Mann= 3 , 0 , 0
       0      .1       0   200.6    .045       0   215.6      .1       0
Bank Sta=200.6,215.6
XS Rating Curve= 0 ,0
Exp/Cntr=0.3,0.1

Type RM Length L Ch R = 1 ,34213   ,24.4,30.5,36.4
XS GIS Cut Line= 4
     1810359.676      416725.816     1810327.124      416564.358
     1810276.342        416402.9      1810150.04      416095.608
#Sta/Elev= 30
       0  1105.7    58.1 1088.39    87.2 1081.23   106.6 1077.41   116.3 1074.61
     126 1072.84     155 1071.88   164.7 1071.21   184.6 1068.87   224.4  1066.8
   232.7 1065.62   244.4  1065.3   247.7 1065.88   264.3 1068.32   284.2 1072.23
     314 1074.74     324 1076.06   343.7 1085.94   363.3 1095.01     373 1097.04
   382.8 1096.29   392.6 1094.97   402.4  1094.4   441.4 1094.72   500.1 1109.45
   548.9  1120.5   617.3  1138.4   636.9 1142.23   656.4 1144.65   666.2 1145.26
#Mann= 3 , 0 , 0
       0      .1       0   232.7    .045       0   247.7      .1       0
Bank Sta=232.7,247.7
XS Rating Curve= 0 ,0
Exp/Cntr=0.3,0.1

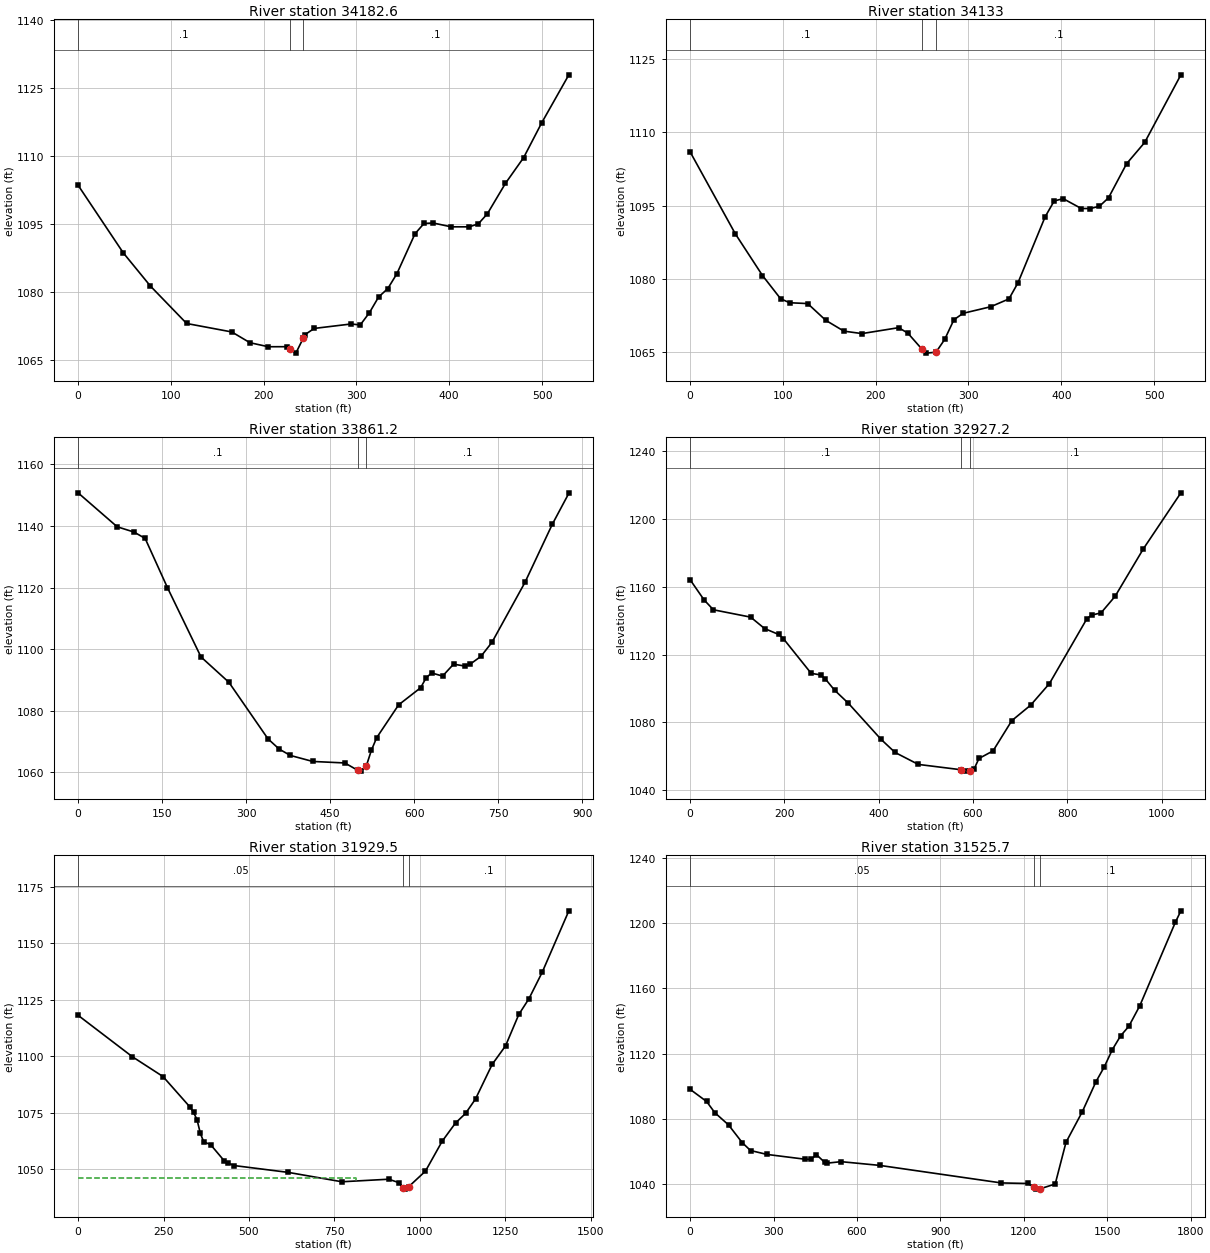
Type RM Length L Ch R = 1 ,34182.6 ,49.4,49.6,49.4
XS GIS Cut Line= 4
      1810368.79      416716.702     1810336.238       416534.41
     1810328.426      416385.973     1810307.592      416191.962
#Sta/Elev= 30
       0 1103.58    48.7 1088.66      78 1081.32     117 1073.07   165.7  1071.2
   185.2 1068.83     205 1067.94   224.8 1067.95   228.6  1067.4   234.7 1066.53
  242.72 1069.85   244.6 1070.62   254.5 1071.98   294.2 1072.96   304.1 1072.75
     314 1075.46   323.9 1078.92   333.8 1080.78   343.6 1084.06   363.1 1092.87
   372.8 1095.14   382.6 1095.25   402.1  1094.4   421.6  1094.4   431.4 1095.07
   441.1 1097.28   460.6    1104   480.2 1109.68   499.7 1117.37   528.9 1127.94
#Mann= 3 , 0 , 0
       0      .1       0   228.6    .045       0  242.72      .1       0
Bank Sta=228.6,242.72
XS Rating Curve= 0 ,0
Exp/Cntr=0.3,0.1

Type RM Length L Ch R = 1 ,34133   ,274.4,271.8,269.6
XS GIS Cut Line= 4
     1810415.318      416718.091     1810382.766      416535.799
     1810374.954      416387.362      1810354.12      416193.351
#Sta/Elev= 30
       0 1105.97    48.7 1089.24      78 1080.72    97.5 1075.98   107.2 1075.16
   126.7 1074.99   146.2 1071.57   165.7 1069.36   185.2 1068.86   224.8 1070.07
   234.7 1068.94     250 1065.65   254.5 1064.87     265 1065.06   274.4 1067.68
   284.3 1071.69   294.2    1073   323.9 1074.34   343.6 1075.94   353.3 1079.21
   382.6  1092.7   392.4 1095.95   402.1 1096.41   421.6  1094.4   431.4  1094.4
   441.1 1094.86   450.9 1096.58   470.4 1103.55   489.9 1107.89   528.9  1121.7
#Mann= 3 , 0 , 0
       0      .1       0     250    .045       0     265      .1       0
Bank Sta=250,265
XS Rating Curve= 0 ,0
Exp/Cntr=0.3,0.1

Type RM Length L Ch R = 1 ,33861.2 ,933.3,934,932.8
XS GIS Cut Line= 4
     1810715.318      416911.754     1810625.474      416492.483
     1810608.547      416389.618     1810539.537      416053.681
#Sta/Elev= 30
       0 1150.74    69.8 1139.72    99.7 1138.02   119.7 1135.95   159.6 1119.94
   219.4 1097.48   269.2 1089.26     339  1070.9     359 1067.58   378.9 1065.52
   418.8 1063.57   476.2 1063.08   499.3 1060.68   504.6 1060.43   514.3 1062.01
   523.6 1067.23     533 1071.28   572.2 1081.94   611.4 1087.48   621.2 1090.68
     631  1092.3   650.6 1091.27   670.2 1095.14   689.8 1094.54   699.6  1095.1
   719.2 1097.69   738.8 1102.24   797.6 1121.65   846.6 1140.58     876  1150.6
#Mann= 3 , 0 , 0
       0      .1       0   499.3    .045       0   514.3      .1       0
Bank Sta=499.3,514.3
XS Rating Curve= 0 ,0
Exp/Cntr=0.3,0.1

Type RM Length L Ch R = 1 ,32927.2 ,996.5,997.7,999.1
XS GIS Cut Line= 3
     1811483.113      416884.844     1811444.101      416303.481
     1811400.648      415847.518
#Sta/Elev= 30
       0  1164.2    29.6  1152.3    49.4 1146.47   128.4 1142.13     158 1135.39
   187.6 1131.94   197.5 1129.53   256.8 1108.96   276.5 1108.09   286.4 1105.81
   306.2  1099.1   335.8 1091.29   404.9 1070.06   434.5 1062.35   483.9 1055.28
   575.2 1052.11   582.7 1051.32   592.6 1051.65   602.6 1052.82   612.5 1058.78
   642.4 1063.25   682.2  1081.1   722.1 1090.22   761.9 1102.93   841.6 1141.29
   851.5 1143.33   871.4 1144.64   901.3 1154.44     961 1182.35  1040.7 1215.44
#Mann= 3 , 0 , 0
       0      .1       0   575.2    .045       0   592.6      .1       0
Bank Sta=575.2,592.6
XS Rating Curve= 0 ,0
Exp/Cntr=0.3,0.1

Type RM Length L Ch R = 1 ,31929.5 ,407.8,403.8,391
XS GIS Cut Line= 5
     1811980.372      417025.324     1812251.205      416608.658
      1812360.58      416262.304      1812360.58      415988.866
     1812350.163      415686.783
#Sta/Elev= 30
       0 1118.09     159 1099.72   248.5 1090.96     328 1077.36   337.9 1075.04
   347.9 1071.92   357.8 1065.77   367.7 1062.02   387.6 1060.83   427.4 1053.68
   437.3  1052.7   457.2 1051.53   614.8 1048.52   771.8 1044.36     909 1045.49
   938.3 1043.98   951.9 1041.79   957.8  1041.1   967.6 1042.21  1016.4 1049.08
  1065.2 1062.29  1104.3 1070.39  1133.6 1074.61  1162.8 1081.02  1211.6 1096.36
  1250.6 1104.53  1289.6  1118.5  1318.9 1125.36  1357.9 1137.14  1435.9 1164.36
#Mann= 3 , 0 , 0
       0     .05       0   951.9    .045       0   967.6      .1       0
#XS Ineff= 2 , 0
          813.09 1046.17
Permanent Ineff=
       F       F
Bank Sta=951.9,967.6
XS Rating Curve= 0 ,0
Exp/Cntr=0.3,0.1

Type RM Length L Ch R = 1 ,31525.7 ,422.3,421.3,405.1
XS GIS Cut Line= 5
     1812027.203      417117.396     1812527.203      416612.188
     1812756.985      416275.035     1812720.092      416005.938
     1812626.777      415643.525
#Sta/Elev= 30
       0 1097.98    59.2 1090.52    88.8 1083.64   138.2  1076.1   187.6 1065.18
   217.2 1060.37   276.4 1057.96   414.6 1054.99   434.4 1054.88   454.1 1057.86
   483.7 1053.11   493.6 1052.62     543 1053.51   681.2 1051.23  1118.8 1040.44
  1215.8 1040.09  1235.2 1037.84  1244.9 1036.63  1257.8  1036.8  1312.8 1039.77
  1351.6  1065.4  1410.1 1084.16  1459.4 1102.68  1488.9 1111.66  1518.4 1122.43
    1548 1130.86  1577.5 1136.71  1616.9 1149.33    1745 1200.73  1764.7 1207.72
#Mann= 3 , 0 , 0
       0     .05       0  1235.2    .045       0  1257.8      .1       0
Bank Sta=1235.2,1257.8
XS Rating Curve= 0 ,0
Exp/Cntr=0.3,0.1

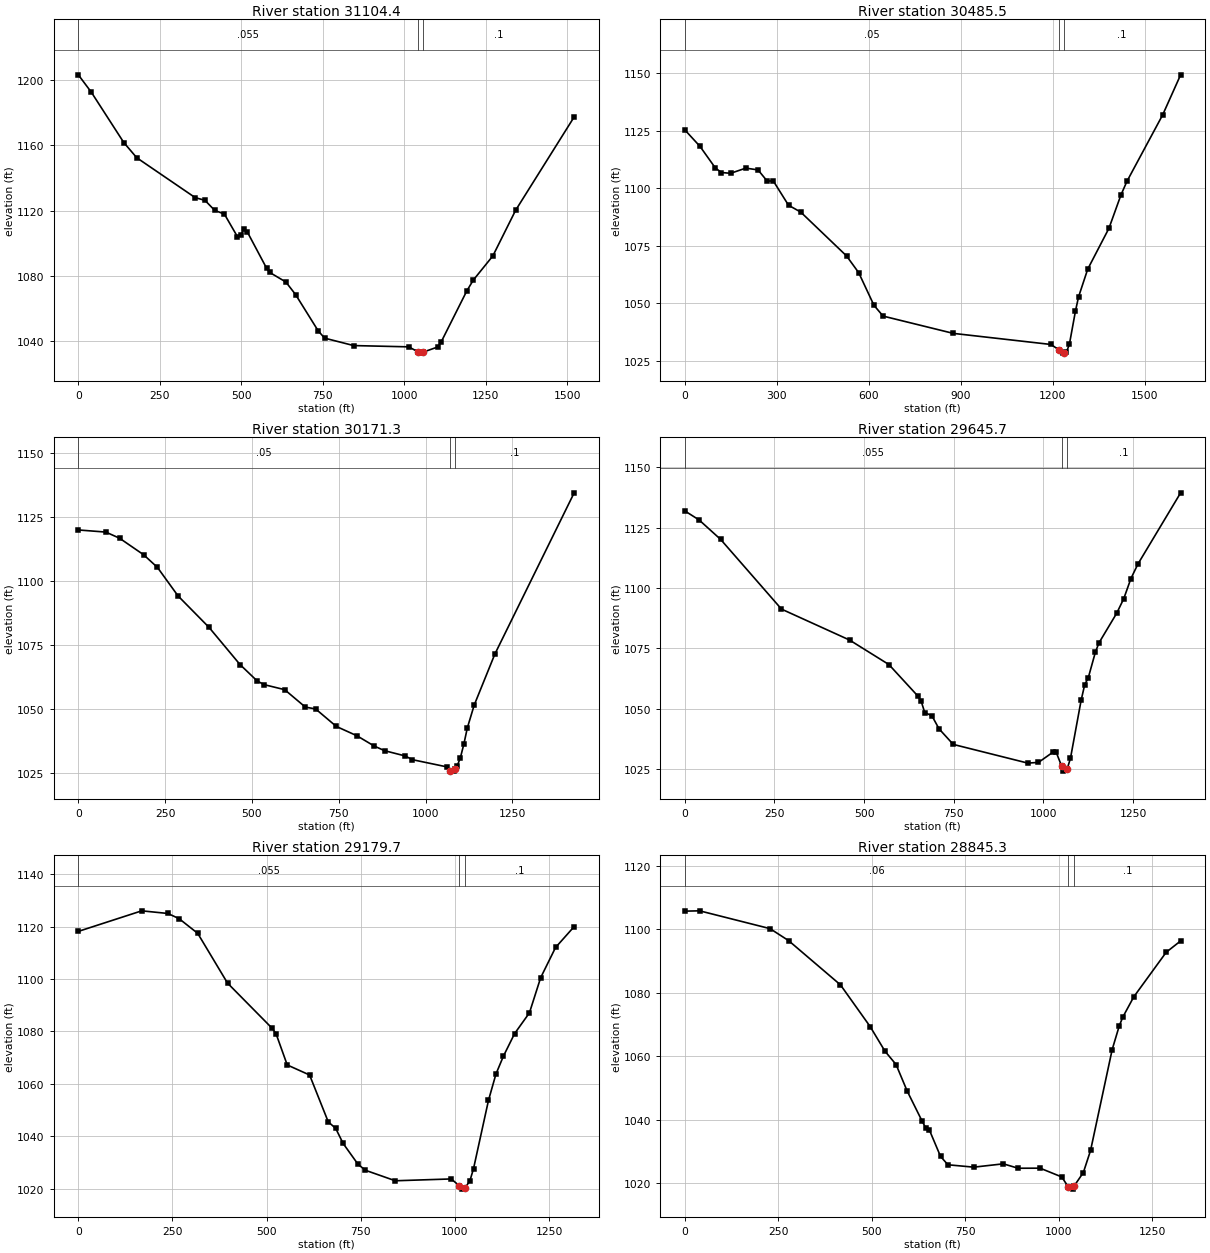
Type RM Length L Ch R = 1 ,31104.4 ,621.4,618.9,615.6
XS GIS Cut Line= 5
     1813188.113      417072.364     1813204.138      416554.939
      1813132.26      416125.171     1813071.497      415853.903
     1812991.201      415576.126
#Sta/Elev= 30
       0 1203.34    39.8 1192.68   139.4 1161.75   179.2  1152.4   358.4 1127.91
   388.2 1126.26   418.1 1120.11     448 1117.77   487.8 1103.97   497.8  1104.8
   507.7 1108.45   517.7 1107.03   577.1 1084.65     587 1081.95   636.5 1076.07
   666.2 1068.38   735.5 1046.11   755.4 1041.59   844.5 1037.03    1013 1036.25
  1041.1 1033.28  1052.7 1032.39  1056.1  1032.9  1102.3 1036.18  1112.3 1039.08
  1191.7 1070.74  1211.5 1077.31  1271.3 1092.13  1341.1 1120.14  1520.6 1177.47
#Mann= 3 , 0 , 0
       0    .055       0  1041.1    .045       0  1056.1      .1       0
Bank Sta=1041.1,1056.1
XS Rating Curve= 0 ,0
Exp/Cntr=0.3,0.1

Type RM Length L Ch R = 1 ,30485.5 ,322.7,314.2,305.7
XS GIS Cut Line= 4
     1813377.645      416860.973     1813572.957       415875.73
     1813442.749      415541.528      1813312.54      415324.514
#Sta/Elev= 30
       0 1125.32    49.7 1118.11    99.4  1108.8   119.3 1106.79   149.2 1106.44
   198.9 1108.69   238.7 1107.92   268.5 1103.07   288.4 1103.14   338.1 1092.57
   377.9 1089.59   527.1 1070.56   566.8 1063.28   616.6 1049.08   646.4  1044.4
   875.1 1036.89  1193.7 1032.07  1220.2 1029.67  1233.6 1028.31  1235.2 1028.36
  1243.5 1028.62  1253.5 1032.07  1273.4  1046.6  1283.4 1052.71  1313.3 1064.78
  1382.6 1082.57  1421.5 1096.97    1441  1102.9  1557.8 1131.86  1616.2 1149.23
#Mann= 3 , 0 , 0
       0     .05       0  1220.2    .045       0  1235.2      .1       0
Bank Sta=1220.2,1235.2
XS Rating Curve= 0 ,0
Exp/Cntr=0.3,0.1

Type RM Length L Ch R = 1 ,30171.3 ,528,525.6,522.8
XS GIS Cut Line= 3
     1814386.622      416298.762     1813945.469      415713.657
     1813477.768      415199.804
#Sta/Elev= 30
       0 1119.91    79.2 1119.08   118.8 1116.68   188.2 1110.21   227.8 1105.29
   287.2 1094.15   376.3 1081.89   465.4  1067.4   514.9 1060.98   534.7 1059.55
   594.1 1057.58   653.6 1050.78   683.3 1050.05   742.7 1043.24   802.3 1039.58
   851.9 1035.58   881.7 1033.77   941.2 1031.71   961.1 1030.28  1060.3 1027.47
  1069.6 1025.95  1080.2 1025.79  1084.6 1026.59  1090.1  1027.6    1100 1031.01
    1110 1036.33  1119.9  1042.6  1139.8 1051.56  1199.3 1071.47  1427.6  1134.4
#Mann= 3 , 0 , 0
       0     .05       0  1069.6    .045       0  1084.6      .1       0
Bank Sta=1069.6,1084.6
XS Rating Curve= 0 ,0
Exp/Cntr=0.3,0.1

Type RM Length L Ch R = 1 ,29645.7 ,471,466.1,460.9
XS GIS Cut Line= 3
     1814856.483      415853.854     1814356.927      415364.699
     1813848.333      414907.678
#Sta/Elev= 30
       0    1132      40 1128.23    99.9 1120.19   269.7  1091.3   459.4  1078.5
   569.3 1068.33   649.2 1055.42   659.2 1053.17   669.2 1048.46   689.2 1047.11
   709.1  1041.7   748.7 1035.25   956.8  1027.5   986.5  1027.8  1026.2 1031.97
  1036.1  1031.9  1051.2  1026.2  1055.9 1024.18  1066.2 1024.97  1075.7 1029.53
  1105.5 1053.61  1115.4    1060  1125.3 1062.84  1145.1 1073.43    1155 1077.28
  1204.6  1089.6  1224.4 1095.66  1244.2 1103.95    1264 1110.03  1382.9 1139.48
#Mann= 3 , 0 , 0
       0    .055       0  1051.2    .045       0  1066.2      .1       0
#XS Ineff= 2 , 0
         1012.55 1030.23
Permanent Ineff=
       F       F
Bank Sta=1051.2,1066.2
XS Rating Curve= 0 ,0
Exp/Cntr=0.3,0.1

Type RM Length L Ch R = 1 ,29179.7 ,334.1,334.3,334.5
XS GIS Cut Line= 3
     1815231.811      415359.671     1814732.388      414969.462
     1814131.821      414644.904
#Sta/Elev= 30
       0 1118.22   168.4 1126.07   237.7 1125.06   267.4 1123.09   316.9 1117.48
   396.1 1098.48     515 1081.16   524.9 1079.16   554.6 1067.23     614 1063.39
   663.5 1045.51   683.3 1043.01     703 1037.26   742.6  1029.3   762.4 1027.01
   841.6 1023.01     990 1023.71  1010.8 1021.19  1019.6 1019.82  1025.8 1020.18
  1039.4 1022.89  1049.3 1027.69  1088.9 1053.69  1108.7 1063.73  1128.5 1070.56
  1158.2 1079.18  1197.7 1087.14  1227.4 1100.52    1267 1112.07  1316.4 1120.05
#Mann= 3 , 0 , 0
       0    .055       0  1010.8    .045       0  1025.8      .1       0
Bank Sta=1010.8,1025.8
XS Rating Curve= 0 ,0
Exp/Cntr=0.3,0.1

Type RM Length L Ch R = 1 ,28845.3 ,327.4,331,332.8
XS GIS Cut Line= 5
     1815205.198      415253.623     1814746.865      414706.748
     1814602.769      414531.397     1814451.728      414446.327
     1814241.656      414418.554
#Sta/Elev= 30
       0 1105.71    39.6 1105.81   227.9  1100.2   277.5 1096.43   416.2 1082.49
   495.5 1069.37   535.2  1061.6   564.9 1057.39   594.6 1049.04   634.3 1039.62
   644.2 1037.45   654.1 1036.74   683.8 1028.45   703.6 1025.81   772.8 1025.06
   851.7 1026.11   891.2 1024.72   950.1 1024.74  1007.9 1021.98  1025.7 1018.79
  1036.8 1018.14  1040.7 1019.06  1065.7 1023.37    1085 1030.33  1142.8 1062.11
    1162 1069.68  1171.6 1072.42  1200.5 1078.71  1287.2 1092.75  1325.8 1096.33
#Mann= 3 , 0 , 0
       0     .06       0  1025.7    .045       0  1040.7      .1       0
Bank Sta=1025.7,1040.7
XS Rating Curve= 0 ,0
Exp/Cntr=0.3,0.1

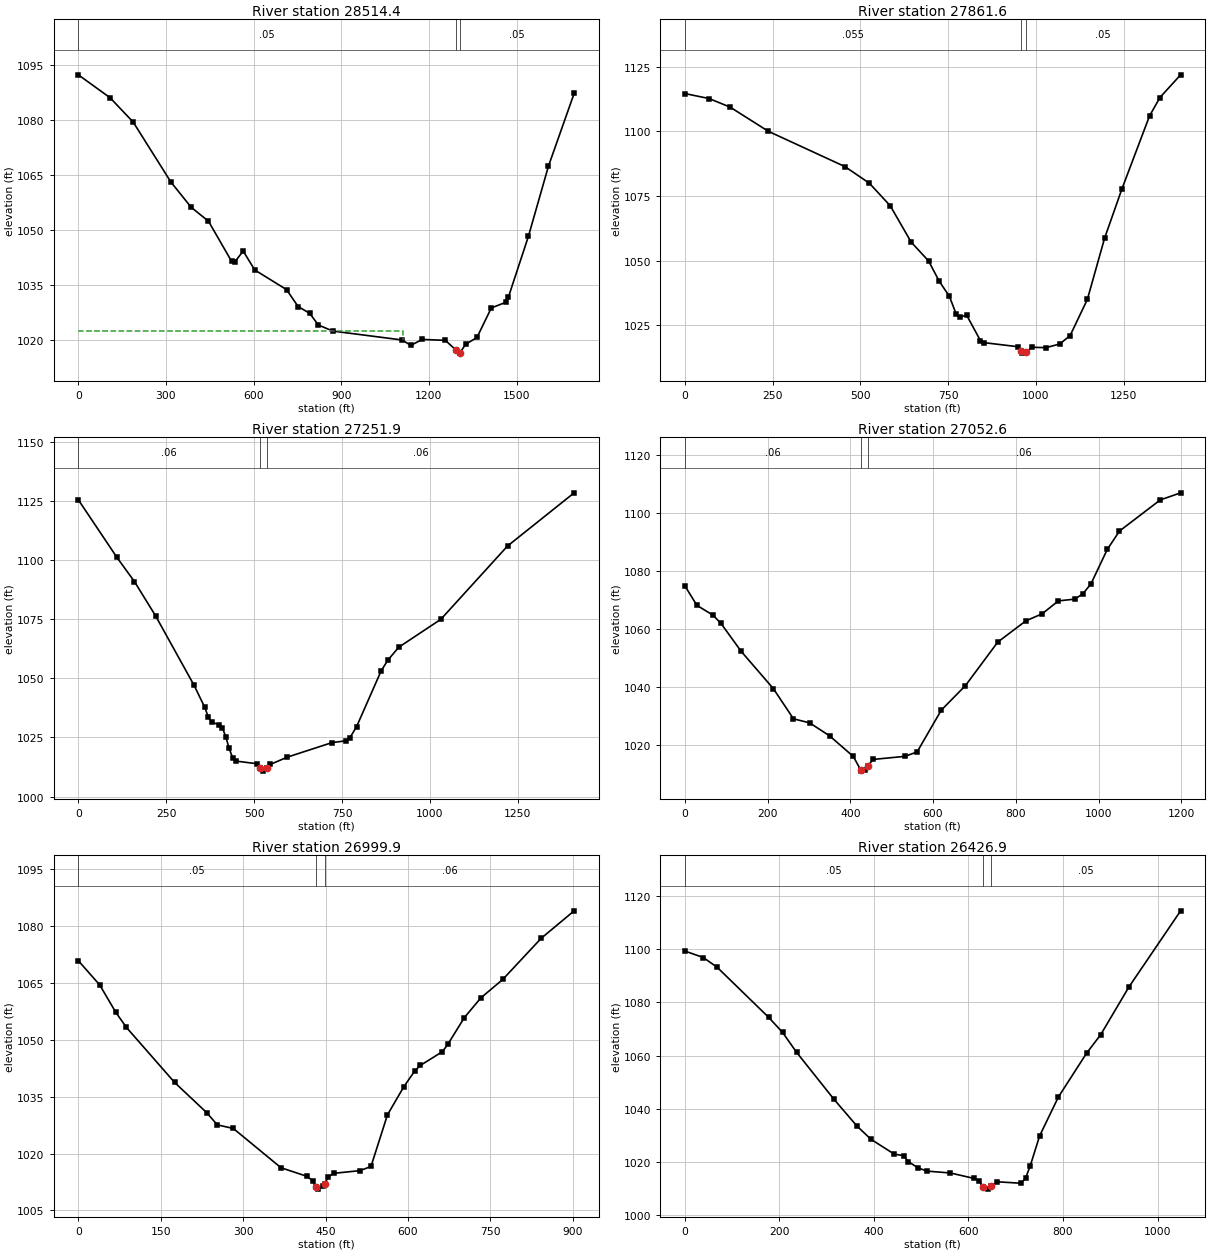
Type RM Length L Ch R = 1 ,28514.4 ,655.8,652.8,651
XS GIS Cut Line= 5
     1815283.016      415265.921     1814851.592      414452.553
     1814651.162      414221.071     1814553.071      414155.099
     1814257.324      413963.914
#Sta/Elev= 30
       0 1092.39   108.9 1086.12   188.1 1079.45   316.8 1063.12   386.1 1056.23
   445.5 1052.41   524.7 1041.45   534.6 1041.19   564.3 1044.27   603.9  1039.1
   712.8 1033.73   752.4 1029.11     792 1027.26   821.7 1024.07   871.2 1022.41
  1108.4 1019.98    1138 1018.51  1177.5 1020.13  1256.4 1019.88  1291.6  1017.3
  1305.7 1016.39  1306.6 1016.49  1325.4 1018.78  1364.7 1020.67  1413.6 1028.72
  1462.5 1030.25  1472.3  1031.7  1540.8 1048.31  1609.2 1067.42  1697.3 1087.34
#Mann= 3 , 0 , 0
       0     .05       0  1291.6    .045       0  1306.6     .05       0
#XS Ineff= 2 , 0
         1111.08 1022.31
Permanent Ineff=
       F       F
Bank Sta=1291.6,1306.6
XS Rating Curve= 0 ,0
Exp/Cntr=0.3,0.1

Type RM Length L Ch R = 1 ,27861.6 ,614.1,609.7,604
XS GIS Cut Line= 4
     1815615.058       414469.48     1815206.196      413847.807
     1814918.002      413679.404     1814606.283      413557.664
#Sta/Elev= 30
       0  1114.7    69.4 1112.74     129 1109.44   238.1 1100.06   456.4 1086.38
   525.8 1079.96   585.3 1071.21   644.9 1057.15   694.5 1049.84   724.2 1042.14
   753.9  1036.1   773.5 1029.14   783.3 1028.18     803 1028.82   842.2    1019
   852.1 1018.22   950.2 1016.61     957  1014.9     960 1014.15     972 1014.45
   989.5 1016.42  1028.8 1016.27    1068 1017.69  1097.6 1020.92  1146.8 1034.95
    1196 1058.72  1245.2 1077.72  1323.9 1106.01  1353.5 1113.15  1412.5 1121.94
#Mann= 3 , 0 , 0
       0    .055       0     957    .045       0     972     .05       0
Bank Sta=957,972
XS Rating Curve= 0 ,0
Exp/Cntr=0.3,0.1

Type RM Length L Ch R = 1 ,27251.9 ,205.7,199.2,192.3
XS GIS Cut Line= 4
     1815829.891      413427.379     1815431.453      413297.171
     1815163.224      413208.629     1814496.557      413448.212
#Sta/Elev= 30
       0  1125.4   109.8 1101.06   159.7 1090.84   219.6  1076.4   329.4 1046.97
   359.3 1037.79   369.3 1033.79   379.2 1031.48   399.2 1030.43   409.2  1029.2
   419.2 1025.39   428.9 1020.38   438.6 1016.49   448.4 1015.03   506.8 1013.94
   516.6 1011.91   526.3 1010.79   536.1  1012.2   545.8 1013.61   594.5 1016.71
   721.6 1022.85   761.5  1023.6   771.5 1024.69   791.4 1029.61   861.3 1053.21
   881.2 1057.86   911.2 1063.13  1030.9 1074.92  1220.5 1105.88    1410 1128.35
#Mann= 3 , 0 , 0
       0     .06       0   516.6    .045       0   536.1     .06       0
Bank Sta=516.6,536.1
XS Rating Curve= 0 ,0
Exp/Cntr=0.3,0.1

Type RM Length L Ch R = 1 ,27052.6 ,52.6,52.8,52.7
XS GIS Cut Line= 5
     1815826.418      413133.108     1815519.127      413082.761
     1815317.738      413077.553      1814958.09      413051.863
      1814633.71      413030.678
#Sta/Elev= 30
       0 1074.84    29.2 1068.05    68.1 1064.66    87.6 1061.79   136.2 1052.18
   214.1  1039.3   262.7 1028.89   301.7  1027.5   349.8 1023.04   407.3  1015.9
  425.29 1011.23   426.5 1010.84   436.1 1011.29   441.7 1012.53   455.3 1014.88
   532.3 1015.94   561.6 1017.47     620 1031.89   678.5 1040.38   756.5 1055.38
   824.7 1062.72   863.7 1065.12     903 1069.59   942.4 1070.19   962.1    1072
   981.8 1075.48  1021.2 1087.34  1050.7 1093.69  1149.2 1104.42  1198.5 1106.88
#Mann= 3 , 0 , 0
       0     .06       0  425.29    .045       0   441.7     .06       0
Bank Sta=425.29,441.7
XS Rating Curve= 0 ,0
Exp/Cntr=0.3,0.1

Type RM Length L Ch R = 1 ,26999.9 ,571.1,573,575
XS GIS Cut Line= 4
     1815826.418      413081.025     1815519.127      413030.678
     1815317.738      413025.469     1814928.849      412997.691
#Sta/Elev= 30
       0 1070.85    38.9 1064.46    68.1 1057.26    87.6 1053.25   175.2 1038.76
   233.5 1030.81     253 1027.57   282.2 1026.61     369 1016.26   416.9 1013.96
   426.5 1012.79   433.2 1011.28   436.1 1010.62   445.7 1011.32   448.2 1011.99
   455.3 1013.89   464.9 1014.78   512.8  1015.5   532.8 1016.59   562.8 1030.21
   592.8 1037.67   612.8 1041.83   622.8 1043.25   662.8 1046.86   672.8 1048.82
   702.8 1055.85   732.8 1061.04   772.8 1065.92   842.7 1076.76   902.7    1084
#Mann= 3 , 0 , 0
       0     .05       0   433.2    .045       0   448.2     .06       0
Bank Sta=433.2,448.2
XS Rating Curve= 0 ,0
Exp/Cntr=0.3,0.1

Type RM Length L Ch R = 1 ,26426.9 ,616.1,606.6,594.8
XS GIS Cut Line= 3
      1816133.71      412598.386     1815626.435      412528.417
     1815089.747      412525.324
#Sta/Elev= 30
       0 1099.29    39.4 1096.82    68.9 1093.11   177.3 1074.39   206.8 1068.74
   236.3 1061.28   315.1  1043.7   364.4 1033.51   393.9 1028.57   443.1 1023.01
   462.8 1022.44   472.7 1020.24   492.4 1017.94   512.1 1016.64   561.8 1015.93
   611.5 1013.91   621.4 1013.04   631.3 1010.82   641.3 1009.87   647.6 1011.09
   661.2 1012.62   710.8 1012.08   720.8 1013.95   730.7 1018.63   750.6 1029.89
   790.4 1044.52     850 1060.95   879.8 1067.88   939.4 1085.78  1048.8 1114.38
#Mann= 3 , 0 , 0
       0     .05       0   631.3    .045       0   647.6     .05       0
Bank Sta=631.3,647.6
XS Rating Curve= 0 ,0
Exp/Cntr=0.3,0.1

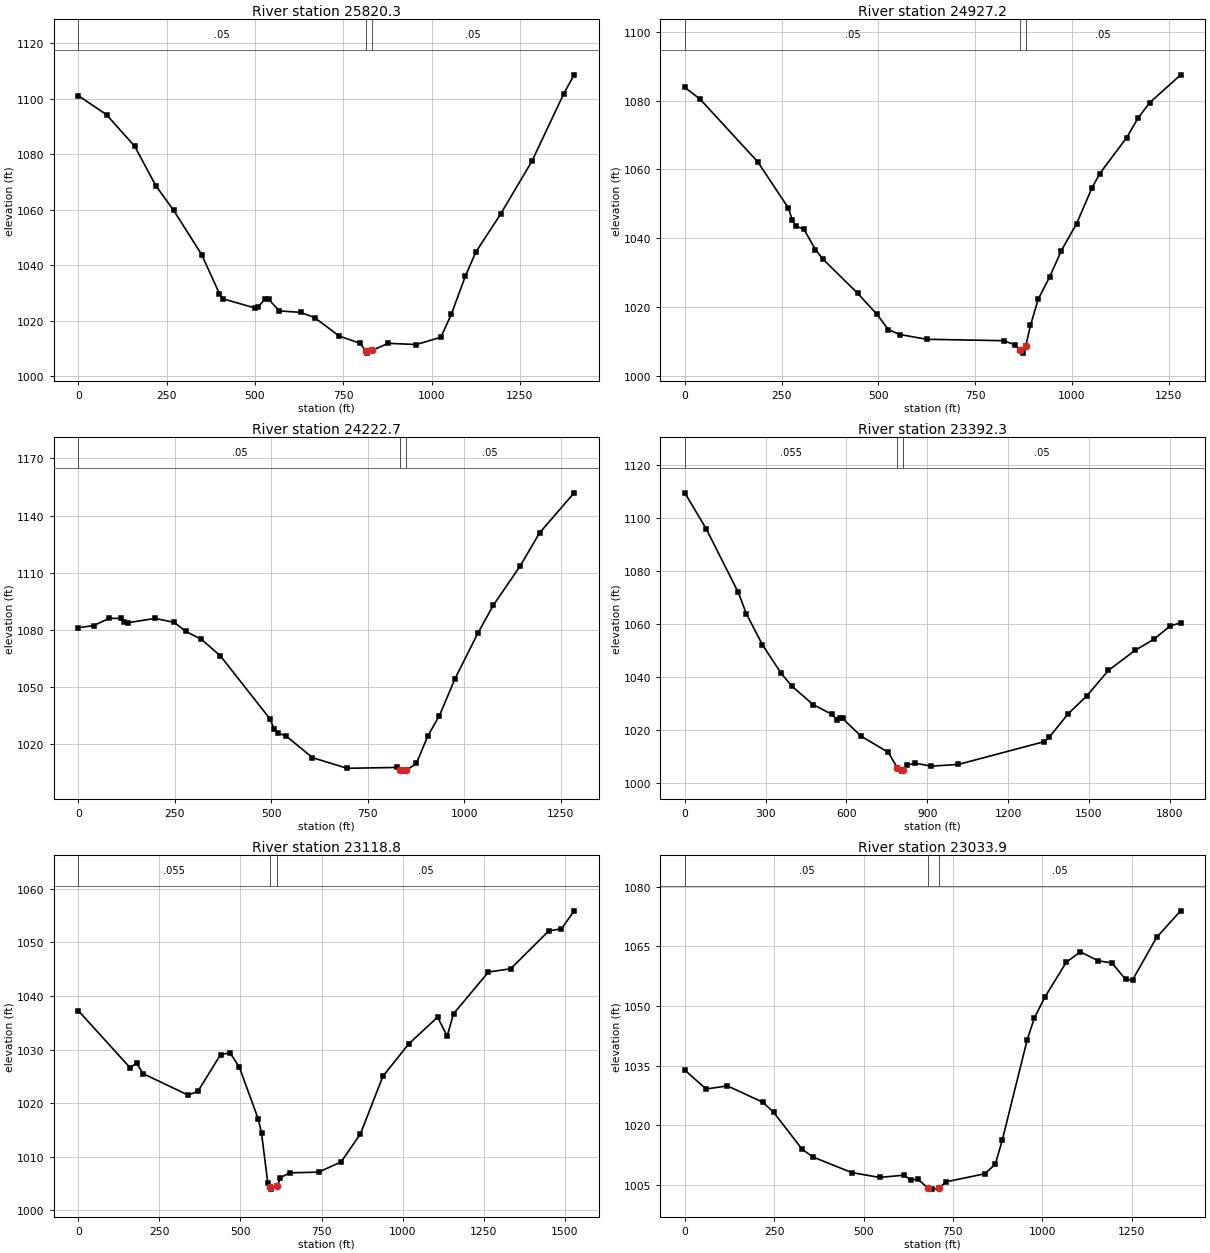
Type RM Length L Ch R = 1 ,25820.3 ,871,893.1,910.2
XS GIS Cut Line= 4
     1816411.488      411858.803     1815697.946      411945.608
     1815413.354      412062.362     1815074.682      412228.594
#Sta/Elev= 30
       0 1101.16    79.9 1094.28   159.7 1082.88   219.6 1068.64   269.6 1059.86
   349.4 1043.82   399.3  1029.8   409.3 1027.94   499.2 1024.64   509.2 1025.07
   529.1  1027.9   539.1 1027.72     569 1023.56     629 1023.05   668.9 1021.16
   738.6  1014.5   798.2 1011.86   813.7 1009.13     818 1008.35  831.43 1009.35
   877.6 1011.88     957 1011.45  1026.4 1014.08  1056.2 1022.42  1095.9 1036.18
  1125.7 1044.85  1195.2 1058.41  1284.5 1077.62  1373.9 1101.76  1403.7 1108.66
#Mann= 3 , 0 , 0
       0     .05       0   813.7    .045       0  831.43     .05       0
Bank Sta=813.7,831.43
XS Rating Curve= 0 ,0
Exp/Cntr=0.3,0.1

Type RM Length L Ch R = 1 ,24927.2 ,704.7,704.5,703.3
XS GIS Cut Line= 3
     1816328.285      411660.452      1815544.11      411276.852
     1815169.431      411115.747
#Sta/Elev= 30
       0 1083.87    39.7 1080.43   188.5 1062.21   267.8 1048.74   277.8 1045.19
   287.7 1043.45   307.5 1042.67   337.3 1036.72   357.1 1033.89   446.4    1024
     496 1017.91   525.8 1013.42   555.5 1011.99     625 1010.61   823.4  1010.2
   853.1 1008.98   865.5 1007.41     873 1006.58   880.5 1008.61   892.9 1014.62
   912.8 1022.25   942.6 1028.77   972.4 1036.32  1012.2 1044.28    1052  1054.7
  1071.9 1058.79  1141.6  1069.3  1171.4 1075.04  1201.2 1079.45  1280.8 1087.53
#Mann= 3 , 0 , 0
       0     .05       0   865.5    .045       0   880.5     .05       0
Bank Sta=865.5,880.5
XS Rating Curve= 0 ,0
Exp/Cntr=0.3,0.1

Type RM Length L Ch R = 1 ,24222.7 ,838.6,830.5,821.3
XS GIS Cut Line= 3
     1816720.646      411271.563     1816240.284      410900.993
     1815622.617      410621.132
#Sta/Elev= 30
       0 1081.14    39.8 1082.26    79.6 1086.02   109.4 1086.04   119.4 1083.92
   129.3 1083.78   198.9    1086   248.6 1083.93   278.5 1079.15   318.3 1075.13
     368 1066.37   497.3 1033.09   507.2 1027.85   517.2 1025.69   537.1  1024.5
   606.7 1012.92   696.4 1007.34   826.1 1007.79   834.8  1006.6     846 1005.85
   849.8 1006.25   875.9  1009.9   905.8  1024.4   935.8 1035.03   975.7  1054.2
  1035.5 1078.37  1075.4 1092.93  1145.2 1113.61    1195 1130.85  1284.8 1151.93
#Mann= 3 , 0 , 0
       0     .05       0   834.8    .045       0   849.8     .05       0
Bank Sta=834.8,849.8
XS Rating Curve= 0 ,0
Exp/Cntr=0.3,0.1

Type RM Length L Ch R = 1 ,23392.3 ,274.1,273.5,272.5
XS GIS Cut Line= 4
     1817024.465      410494.653     1816529.674      410112.709
     1816041.392      410077.987     1815316.566      410117.049
#Sta/Elev= 30
       0 1109.55    79.4 1095.95   198.4 1071.91   228.2 1063.88   287.7 1052.18
   357.2 1041.37   396.9  1036.5   476.2 1029.47   545.7 1025.81   565.5 1023.62
   575.4 1024.54   585.4 1024.24     655 1017.49   754.9 1011.45  789.09 1005.57
   804.9 1004.31   808.8 1004.88   824.9 1006.54   854.8 1007.31   914.8  1006.2
  1014.7 1006.83  1333.3 1015.43  1353.2 1017.18  1422.8    1026  1492.4 1032.77
    1572 1042.37  1671.4 1049.98    1741 1054.16  1800.7 1059.13  1840.4 1060.42
#Mann= 3 , 0 , 0
       0    .055       0  789.09    .045       0   808.8     .05       0
Bank Sta=789.09,808.8
XS Rating Curve= 0 ,0
Exp/Cntr=0.3,0.1

Type RM Length L Ch R = 1 ,23118.8 ,84.8,84.8,84.8
XS GIS Cut Line= 6
      1816781.41      410166.962     1816440.698      409906.546
     1816343.042      409863.143     1816197.642      409856.632
     1815765.785      409793.698      1815372.99      409672.171
#Sta/Elev= 30
       0 1037.25   159.6 1026.62   179.5  1027.5   199.5 1025.52   339.1  1021.5
     369 1022.25   438.6 1029.07   467.7  1029.4   496.8 1026.67   555.1 1016.99
   564.8 1014.44   584.2 1005.14  591.01 1004.32   593.9 1003.98   613.6 1004.51
     623 1006.13   652.1 1007.02   740.8 1007.15   810.2 1009.05   869.7 1014.27
   939.1 1025.02  1018.5 1031.05  1107.8 1036.06  1137.2  1032.5  1156.8 1036.67
  1264.5 1044.47    1333 1045.07  1450.5 1052.13  1489.7 1052.53  1528.8 1055.88
#Mann= 3 , 0 , 0
       0    .055       0  591.01    .045       0   613.6     .05       0
Bank Sta=591.01,613.6
XS Rating Curve= 0 ,0
Exp/Cntr=0.3,0.1

Type RM Length L Ch R = 1 ,23033.9 ,222.7,248.7,275
XS GIS Cut Line= 6
     1816857.365      410119.219     1816494.951       409824.08
     1816397.295      409780.678     1816251.896      409774.167
     1815820.038      409711.233     1815603.024      409633.108
#Sta/Elev= 30
       0 1033.89    59.7 1029.15   119.3 1029.93   218.8  1025.8   248.6 1023.28
   328.2 1014.01     358 1012.07   467.4 1008.13   545.1 1006.92   613.1 1007.49
   632.5 1006.28   651.9 1006.48     681 1004.16   690.7 1003.98  711.25 1004.16
   729.7  1005.8   838.8 1007.83   868.6 1010.23   888.4 1016.43   957.8 1041.55
   977.7 1046.98  1007.4 1052.28    1067 1061.01  1106.6 1063.64  1156.2 1061.37
  1194.7 1060.85  1233.1 1056.69  1252.3 1056.54  1319.6 1067.24  1386.9 1073.94
#Mann= 3 , 0 , 0
       0     .05       0     681    .045       0  711.25     .05       0
Bank Sta=681,711.25
XS Rating Curve= 0 ,0
Exp/Cntr=0.3,0.1