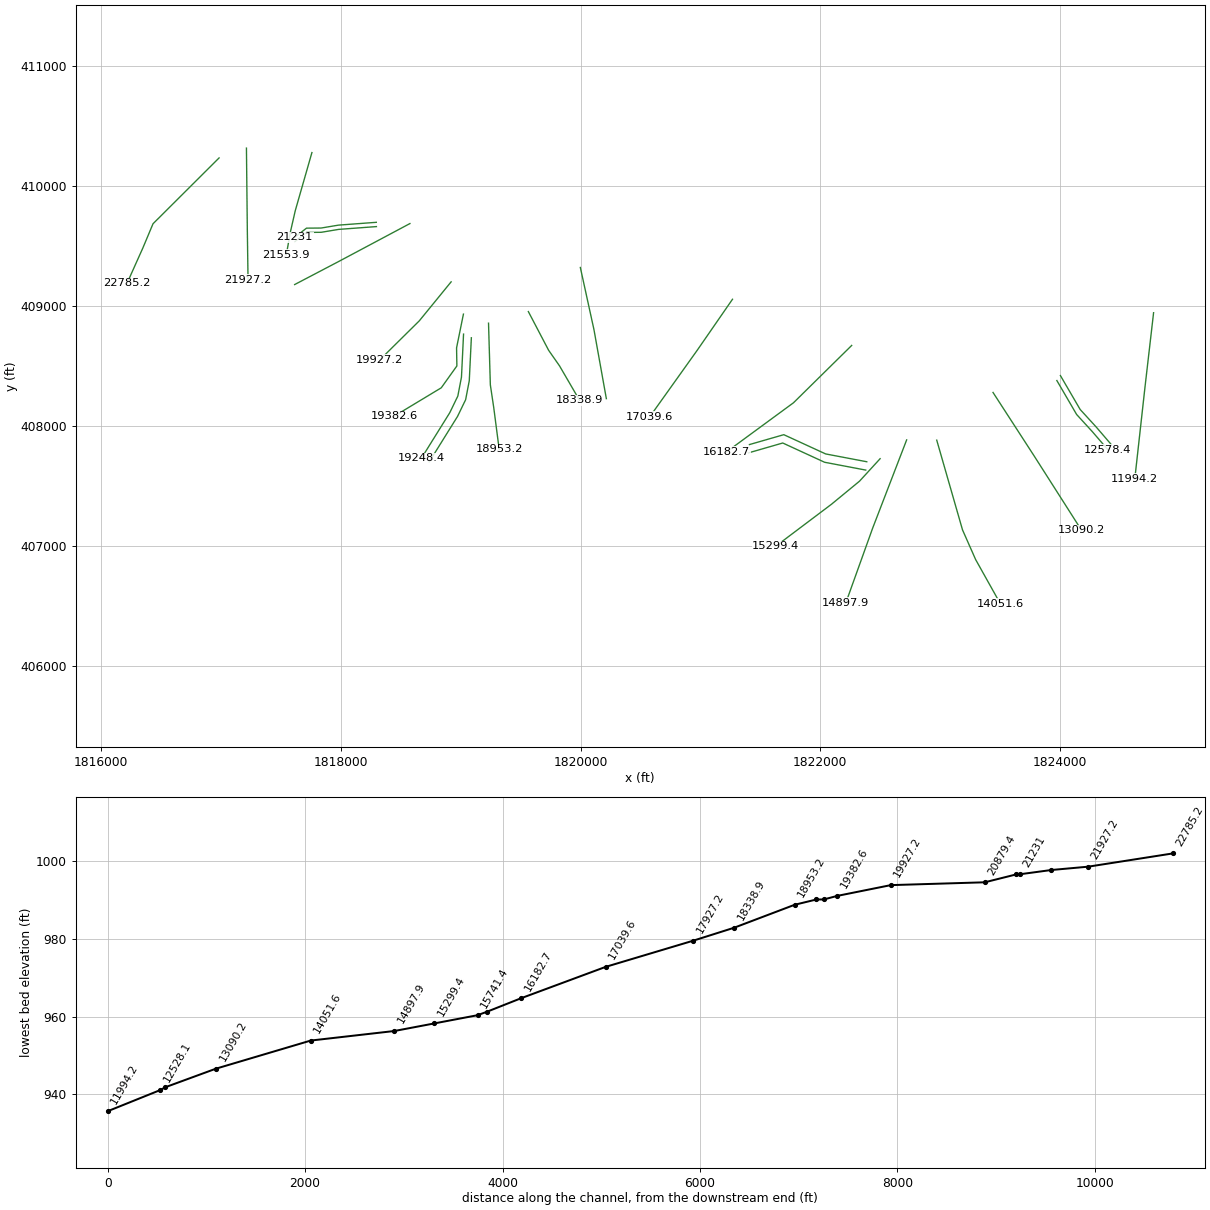
HEC-RAS study DentsRun.prj: DentsRun

--- DentsRun.g01 (geometry) --- (continued)

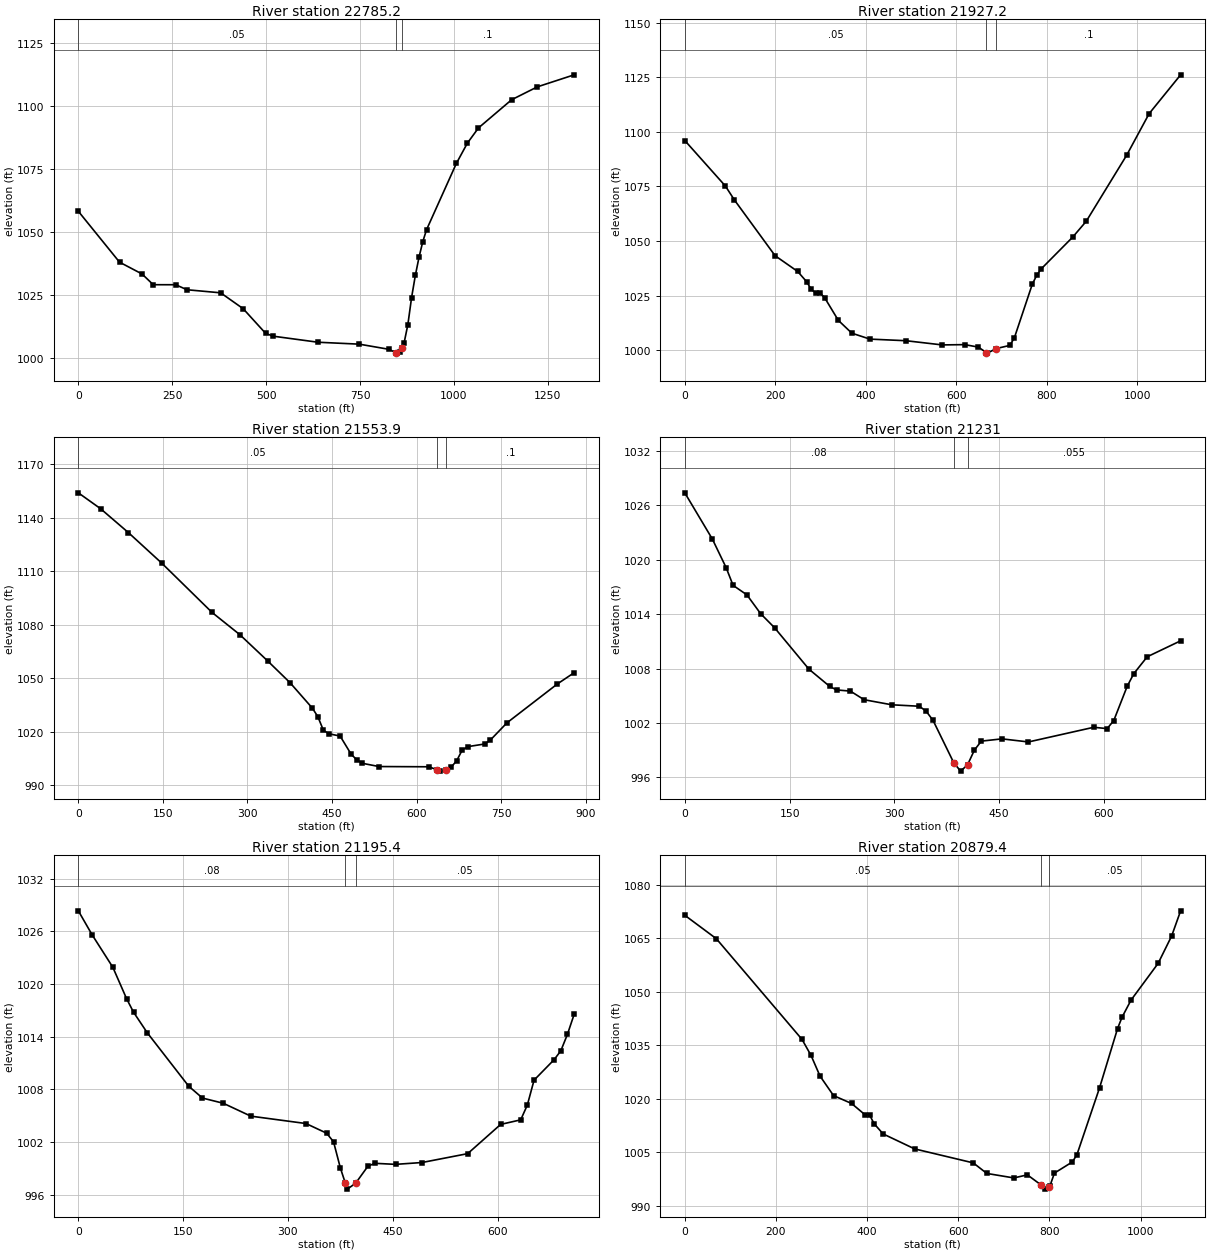
Type RM Length L Ch R = 1 ,22785.2 ,848.6,858,866.9
XS GIS Cut Line= 4
     1816983.233      410236.407     1816432.017      409687.362
     1816347.382      409485.539     1816215.004        409190.4
#Sta/Elev= 30
       0 1058.38   109.7 1038.18   169.6 1033.49   199.5 1029.23   259.3 1029.22
   289.3 1027.23     379 1026.01   438.9 1019.71   498.7 1009.92   518.7  1008.8
   638.4 1006.39   748.1 1005.63   827.7 1003.57  845.38 1002.25   847.4 1002.07
   857.6 1002.32   862.4 1004.19   867.5 1006.17   877.5 1013.42   887.4 1024.15
   897.4 1032.92   907.3 1040.22   917.3 1046.36   927.2 1051.05  1006.7  1077.4
  1036.1 1085.47  1065.5 1091.47  1153.7 1102.65  1222.3 1107.78  1320.3 1112.55
#Mann= 3 , 0 , 0
       0     .05       0  845.38    .045       0   862.4      .1       0
Bank Sta=845.38,862.4
XS Rating Curve= 0 ,0
Exp/Cntr=0.3,0.1

Type RM Length L Ch R = 1 ,21927.2 ,378.3,373.3,367.9
XS GIS Cut Line= 3
     1817211.587      410318.251      1817218.88      409639.505
     1817224.932      409222.138
#Sta/Elev= 30
       0 1095.99    89.8 1075.14   109.8 1068.74   199.6 1043.26   249.6 1036.03
   269.5 1031.31   279.5 1027.85   289.5 1026.18   299.5 1026.09   309.4 1023.95
   339.4 1013.66   369.3 1007.78   409.3 1005.07   489.1 1004.33     569 1002.41
   618.9 1002.54   648.8 1001.42  666.71  998.92   668.8  998.65   688.7 1000.75
   718.5 1002.18   728.5 1005.58   768.2 1030.17   778.2 1034.36   788.1 1037.25
   857.7 1051.79   887.5 1059.01   976.9 1089.26  1026.6 1108.31  1096.2 1126.07
#Mann= 3 , 0 , 0
       0     .05       0  666.71    .045       0   688.7      .1       0
Bank Sta=666.71,688.7
XS Rating Curve= 0 ,0
Exp/Cntr=0.3,0.1

Type RM Length L Ch R = 1 ,21553.9 ,351,322.9,272.1
XS GIS Cut Line= 4
     1817757.846      410281.112     1817618.957      409796.737
      1817577.29      409614.445     1817544.304      409428.681
#Sta/Elev= 30
       0 1153.94    39.5 1145.02    88.9  1131.6   148.2 1114.42   237.1 1086.86
   286.5 1074.36   335.9 1059.61   375.4 1047.46     415  1033.2   424.8 1028.41
   434.7 1020.75   444.6 1018.74   464.4 1017.47   484.1 1007.22     494 1004.15
   503.9 1002.18   533.4 1000.36     622 1000.23   636.3  998.54   641.7  997.79
  652.88  998.37   661.4 1000.01   671.2 1003.64     681 1009.61   690.9 1011.53
   720.7 1013.01   730.6 1015.12   760.4 1024.89   849.8  1046.7   879.6 1053.02
#Mann= 3 , 0 , 0
       0     .05       0   636.3    .045       0  652.88      .1       0
Bank Sta=636.3,652.88
XS Rating Curve= 0 ,0
Exp/Cntr=0.3,0.1

Type RM Length L Ch R = 1 ,21231   ,35.3,35.6,58.7
XS GIS Cut Line= 5
     1818295.172      409699.514     1817980.068      409676.077
     1817834.235      409651.771     1817712.707      409650.903
     1817614.617      409574.514
#Sta/Elev= 30
       0 1027.39    39.5 1022.28    59.2 1019.13    69.1 1017.18    88.9 1016.13
   108.6 1014.05   128.4 1012.51   177.7 1007.93   207.4 1006.03   217.2 1005.64
     237 1005.51   256.7 1004.56   296.2    1004   335.7 1003.84   345.5 1003.29
   355.4 1002.27     385   997.6   394.8  996.68   404.7  997.37   414.5     999
   424.4  999.99     454 1000.24   491.9   999.9   585.4 1001.52   604.5 1001.37
     614 1002.26   633.2 1006.04   642.7 1007.44   661.9  1009.3   709.7 1011.06
#Mann= 3 , 0 , 0
       0     .08       0     385    .045       0   404.7    .055       0
Bank Sta=385,404.7
XS Rating Curve= 0 ,0
Exp/Cntr=0.3,0.1

Type RM Length L Ch R = 1 ,21195.4 ,307.8,316,323.2
XS GIS Cut Line= 5
      1818296.04      409663.924     1817980.936      409640.487
     1817835.103      409616.181     1817713.575      409615.313
     1817615.485      409538.924
#Sta/Elev= 30
       0 1028.33    19.8 1025.59    49.4  1021.9    69.1 1018.32      79 1016.79
    98.7 1014.44     158 1008.36   177.7 1007.01   207.4 1006.42   246.9 1004.95
   325.8 1004.11   355.4 1003.01   365.3 1002.03   375.1  999.04   381.9  997.39
     385  996.64   396.9  997.31   414.5  999.25   424.4  999.58     454  999.46
   491.9  999.67   557.3 1000.68   604.5 1004.01   633.2 1004.53   642.7 1006.22
   652.3 1009.05     681 1011.38   690.6 1012.39   700.1 1014.27   709.7 1016.55
#Mann= 3 , 0 , 0
       0     .08       0   381.9    .045       0   396.9     .05       0
Bank Sta=381.9,396.9
XS Rating Curve= 0 ,0
Exp/Cntr=0.3,0.1

Type RM Length L Ch R = 1 ,20879.4 ,942.9,952.2,959.1
XS GIS Cut Line= 3
     1818575.554      409689.098     1817981.804      409373.125
     1817613.748      409180.417
#Sta/Elev= 30
       0 1071.42    69.2 1064.85   257.2 1036.61     277 1032.12   296.7 1026.33
   326.4 1020.85     366 1018.64   395.6 1015.46   405.5 1015.41   415.4 1012.97
   435.2  1010.1   504.4  1005.9     633 1001.98   662.7  999.02     722  997.76
   751.7  998.62   781.4  995.83   791.3  994.62   798.1  995.23   801.2  995.51
   811.1  999.12   850.6 1002.26   860.5  1004.3     910 1022.99   949.6 1039.65
   959.4 1042.82   979.2 1047.64  1038.6 1057.93  1068.3 1065.61    1088 1072.67
#Mann= 3 , 0 , 0
       0     .05       0   781.4    .045       0   798.1     .05       0
Bank Sta=781.4,798.1
XS Rating Curve= 0 ,0
Exp/Cntr=0.3,0.1

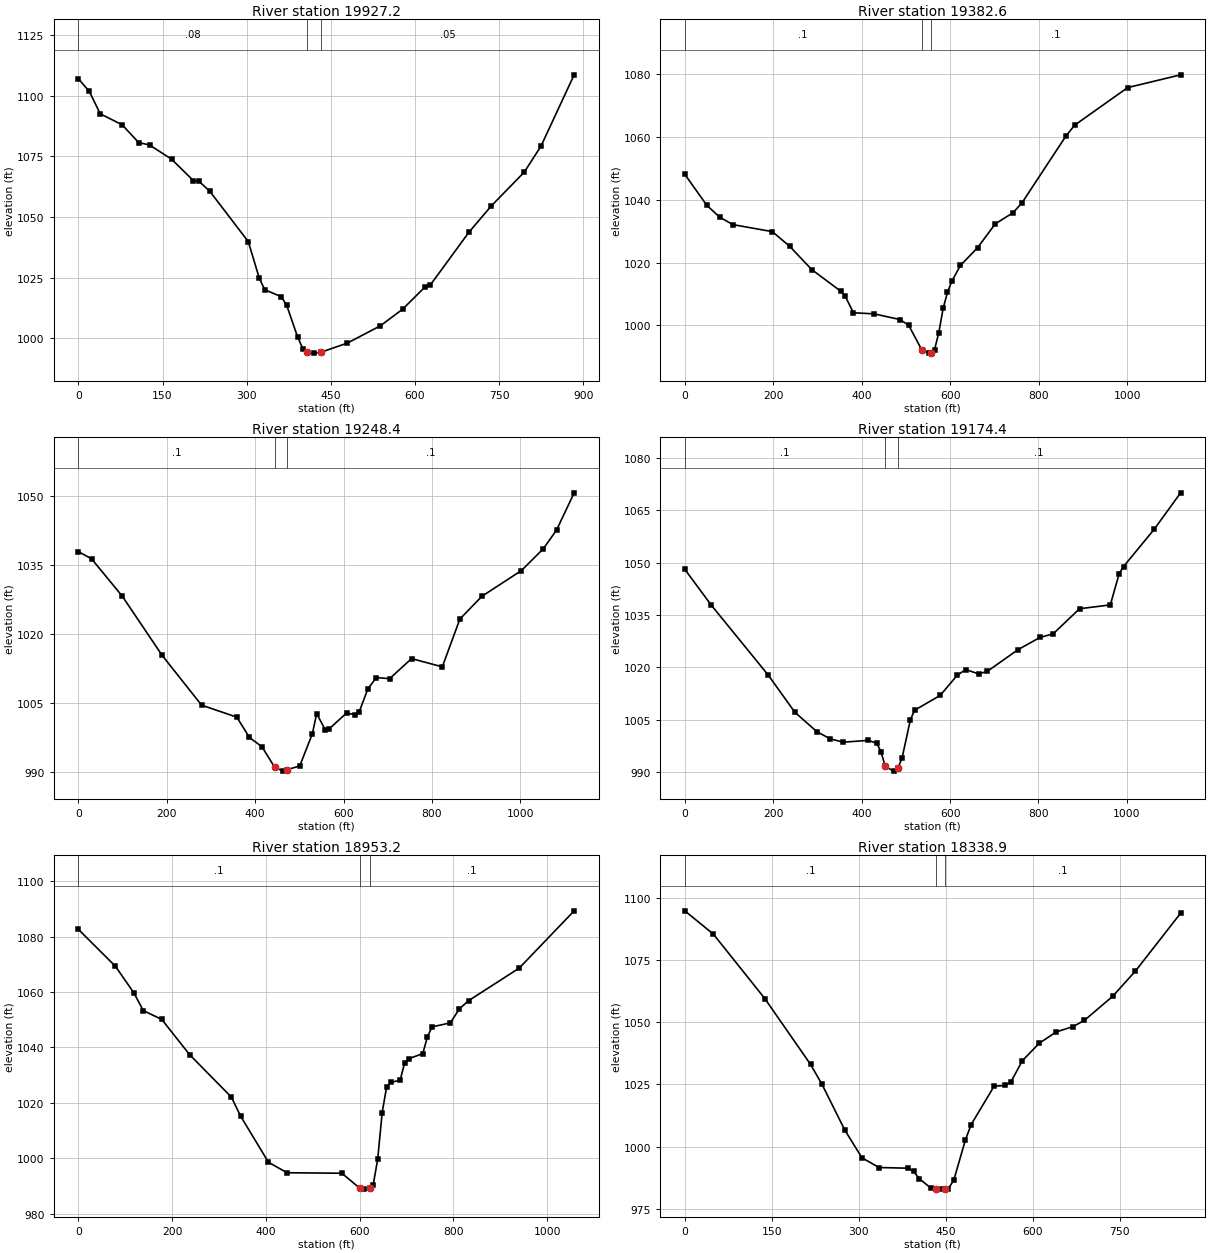
Type RM Length L Ch R = 1 ,19927.2 ,541,544.6,548.8
XS GIS Cut Line= 3
     1818919.304      409202.987     1818653.487      408877.655
     1818323.818      408551.945
#Sta/Elev= 30
       0 1106.96    19.5 1101.71    39.1 1092.47    78.2 1087.95   107.5 1080.63
     127 1079.63   166.1 1073.79   205.2 1064.93   214.9 1064.69   234.5 1060.51
   302.9 1039.81   322.4 1024.82   332.2 1020.03   361.5 1017.14   371.3 1013.61
   390.8 1000.51   400.6  995.44   408.3  994.25   420.1  993.89  431.71  994.21
   479.3  998.01   538.4 1005.16   577.9 1011.99   617.3 1021.03   627.2 1021.93
   696.2 1043.74   735.6 1054.45   794.8 1068.49   824.4 1079.13   883.6 1108.54
#Mann= 3 , 0 , 0
       0     .08       0   408.3    .045       0  431.71     .05       0
Bank Sta=408.3,431.71
XS Rating Curve= 0 ,0
Exp/Cntr=0.3,0.1

Type RM Length L Ch R = 1 ,19382.6 ,121.1,134.2,144.7
XS GIS Cut Line= 5
     1819022.038      408934.179     1818964.747      408652.929
     1818967.351      408501.887     1818837.143      408319.595
     1818443.913      408082.616
#Sta/Elev= 30
       0 1048.12    49.5 1038.29    79.2 1034.41   108.9 1032.08     198 1029.84
   237.5 1025.12     287 1017.75   353.1  1010.8   362.6 1009.27   381.4 1003.98
   428.6 1003.61   486.8  1001.8   506.3  999.97   535.5  992.24   552.9   991.1
   556.7   991.3   564.7  992.17   574.4  997.64   584.2 1005.39   593.9 1010.46
   603.7    1014   623.2 1019.05   662.1 1024.73     702 1032.32     742 1035.85
   761.9  1038.9   861.7  1060.3   881.7 1063.81  1001.5 1075.78  1121.2 1079.85
#Mann= 3 , 0 , 0
       0      .1       0   535.5    .045       0   556.7      .1       0
Bank Sta=535.5,556.7
XS Rating Curve= 0 ,0
Exp/Cntr=0.3,0.1

Type RM Length L Ch R = 1 ,19248.4 ,78.7,74.1,72.9
XS GIS Cut Line= 5
     1819023.037      408767.223     1819005.676       408409.15
     1818975.294       408250.73     1818908.019      408111.841
     1818671.474      407732.066
#Sta/Elev= 30
       0 1037.98    29.9 1036.42    99.6 1028.25   189.2 1015.44   278.8 1004.55
   358.5 1001.94     387  997.52   415.4  995.49   443.9  991.05   462.9  990.19
   472.4  990.52   500.8  991.31   529.4  998.34   539.1 1002.72   558.4   999.2
     568  999.45   606.6 1002.83   625.9 1002.49   635.5 1003.15   654.8 1008.08
   674.1 1010.57     704 1010.31   753.7 1014.69   823.3 1012.89     863  1023.3
   912.8 1028.25  1002.2 1033.86  1051.9 1038.61  1081.8  1042.7  1121.5 1050.78
#Mann= 3 , 0 , 0
       0      .1       0   443.9    .045       0   472.4      .1       0
Bank Sta=443.9,472.4
XS Rating Curve= 0 ,0
Exp/Cntr=0.3,0.1

Type RM Length L Ch R = 1 ,19174.4 ,214.2,221.2,229
XS GIS Cut Line= 5
     1819088.141      408736.841      1819070.78      408378.768
     1819040.398      408220.348     1818973.123      408081.459
     1818736.578      407701.684
#Sta/Elev= 30
       0  1048.1    59.8 1037.84   189.2 1017.67     249 1007.07   298.7 1001.52
   328.6  999.47   358.5  998.49   415.4  999.02   434.4  998.16   443.9  995.71
   453.4  991.52   472.4  990.19   481.8  991.01   491.3  993.86   510.3 1004.97
   519.8 1007.66   577.7 1011.92   616.2  1017.7   635.5 1019.34   664.5 1018.09
   684.1 1018.81   753.7 1025.05   803.4 1028.55   833.2 1029.59   892.9 1036.79
   962.5 1037.89   982.4 1046.83   992.3 1048.89  1061.9 1059.62  1121.5 1070.05
#Mann= 3 , 0 , 0
       0      .1       0   453.4    .045       0   481.8      .1       0
Bank Sta=453.4,481.8
XS Rating Curve= 0 ,0
Exp/Cntr=0.3,0.1

Type RM Length L Ch R = 1 ,18953.2 ,603.6,614.3,624.7
XS GIS Cut Line= 4
      1819231.37      408858.368     1819246.561      408344.046
     1819274.773      408155.243     1819320.346      407805.851
#Sta/Elev= 30
       0  1082.7    79.2 1069.33   118.7 1059.68   138.5 1053.35   178.1 1050.12
   237.5 1037.39   326.5 1022.07   346.3 1015.16   405.7  998.52   445.3  994.74
   562.3  994.56   600.4  989.16     610  988.82   622.5  989.37   629.1  990.45
   638.6  999.54   648.2 1016.49   657.7 1025.73   667.3 1027.48   686.4  1028.1
   695.9 1034.26   705.4 1035.97   734.8 1037.78   744.6 1043.73   754.4 1047.43
   793.5 1048.89   813.1 1053.98   832.7 1056.94   940.4 1068.65  1057.8 1089.38
#Mann= 3 , 0 , 0
       0      .1       0   600.4    .045       0   622.5      .1       0
Bank Sta=600.4,622.5
XS Rating Curve= 0 ,0
Exp/Cntr=0.3,0.1

Type RM Length L Ch R = 1 ,18338.9 ,420.7,411.8,401.9
XS GIS Cut Line= 4
     1819563.705      408955.012     1819732.976      408632.095
     1819824.122      408501.887     1819990.788      408215.429
#Sta/Elev= 30
       0 1094.82    49.3 1085.44     138 1059.53   216.8 1033.07   236.5 1025.08
   275.9 1006.64   305.5  995.49     335  991.58   384.5  991.31   394.4     990
   404.3  987.13   424.2  983.31   433.7  982.92   444.1  982.89   448.7  982.89
     454  982.89   463.9  986.55   483.8 1002.63   493.7 1008.81   533.3 1024.26
   552.8 1024.58   562.5 1026.07     582 1034.51   611.3 1041.58   640.5 1046.11
   669.7 1048.28   689.2 1050.78     738 1060.48     777 1070.57     855 1093.87
#Mann= 3 , 0 , 0
       0      .1       0   433.7    .045       0   448.7      .1       0
Bank Sta=433.7,448.7
XS Rating Curve= 0 ,0
Exp/Cntr=0.3,0.1

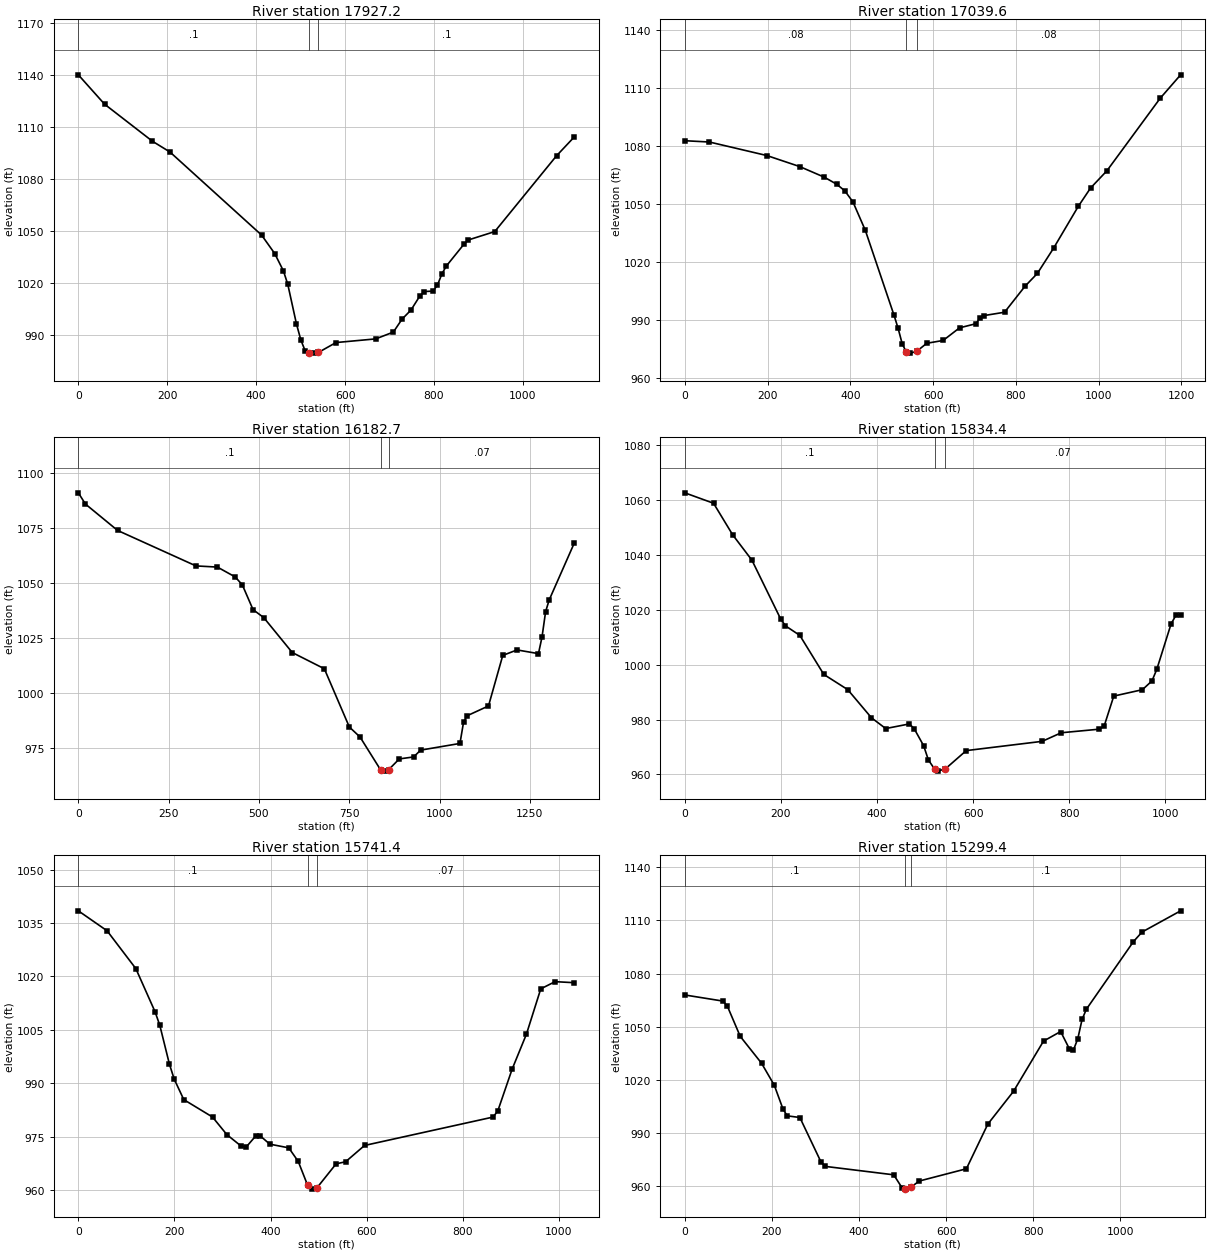
Type RM Length L Ch R = 1 ,17927.2 ,906.6,887.5,869.4
XS GIS Cut Line= 3
     1819997.429      409322.778     1820110.955      408805.077
     1820214.443      408229.028
#Sta/Elev= 30
       0 1140.11    58.9  1123.2   166.8 1101.78   206.1 1095.59   412.2 1047.67
   441.7 1037.03   461.3 1027.02   471.1 1019.29   490.7  996.34   500.6   987.1
   510.4  980.78  519.88  979.63     530  979.57   539.9  979.95   579.6  985.67
   668.9  987.78   708.6  991.71   728.4  999.25   748.2  1004.4   768.1 1012.49
     778  1015.1   797.8 1015.35   807.8  1018.8   817.7 1025.21   827.6 1029.76
   867.3 1042.36   877.2 1044.85   936.7 1049.69  1075.6 1093.39  1115.3 1104.21
#Mann= 3 , 0 , 0
       0      .1       0  519.88    .045       0   539.9      .1       0
Bank Sta=519.88,539.9
XS Rating Curve= 0 ,0
Exp/Cntr=0.3,0.1

Type RM Length L Ch R = 1 ,17039.6 ,864.1,857,849.7
XS GIS Cut Line= 3
      1821266.96      409058.021       1820973.7      408634.083
     1820577.059      408078.471
#Sta/Elev= 30
       0 1082.57    59.5  1081.9   198.3 1074.91   277.6 1069.22     337 1063.74
   366.8 1060.12   386.6  1056.7   406.4 1050.92   436.2 1036.29   505.6   992.4
   515.5  985.63   525.4   977.6   535.3  973.39   545.2  972.81  560.17  973.69
   584.7   977.9   624.3  979.36   663.9  985.87   703.5  988.01   713.4  990.95
   723.2  992.22   772.7  993.94   822.2 1007.38   851.9 1013.97   891.4 1027.12
   950.8 1048.62   980.5 1058.11  1020.1 1067.05  1148.7 1104.48  1198.2 1116.62
#Mann= 3 , 0 , 0
       0     .08       0   535.3    .045       0  560.17     .08       0
Bank Sta=535.3,560.17
XS Rating Curve= 0 ,0
Exp/Cntr=0.3,0.1

Type RM Length L Ch R = 1 ,16182.7 ,377.2,348.3,313.5
XS GIS Cut Line= 3
     1822261.246      408672.682     1821776.051      408194.951
     1821218.457      407785.981
#Sta/Elev= 30
       0 1090.99    19.7 1085.89   108.6 1073.93   325.6 1057.83   384.9  1057.3
   434.2 1052.83   453.9 1049.23   483.6 1037.99   513.2 1034.38   592.1 1018.53
   680.9 1011.17   750.1  984.75   779.7   980.2  837.21  965.14   848.8  964.72
   858.7  965.34   888.4  970.26   927.9  971.15   947.6  974.25  1056.3  977.28
  1066.2   986.9    1076  989.83  1135.3   994.3  1174.8 1017.23  1214.4 1019.71
  1273.6 1018.03  1283.5 1025.64  1293.4  1037.1  1303.3  1042.4  1372.4 1068.08
#Mann= 3 , 0 , 0
       0      .1       0  837.21    .045       0   858.7     .07       0
Bank Sta=837.21,858.7
XS Rating Curve= 0 ,0
Exp/Cntr=0.3,0.1

Type RM Length L Ch R = 1 ,15834.4 ,93.5,93,99.8
XS GIS Cut Line= 4
     1822387.186      407702.987     1822044.304      407768.091
     1821694.912      407928.681     1821408.453      407846.216
#Sta/Elev= 30
       0  1062.6    59.8  1058.8    99.7 1047.28   139.6 1038.08   199.4 1016.66
   209.4 1014.14   239.3 1010.67   289.2  996.44     339   990.9   388.4  980.64
     418  976.72   467.3  978.41   477.2  976.68   496.9  970.48   506.8  965.28
  519.86  961.91   526.5  961.21  542.12  962.04   585.6  968.69   743.5  972.06
   783.2  975.19   862.7   976.5   872.6  977.68   892.5  988.55   952.1  990.88
     972  994.08     982  998.28  1011.8 1014.88  1021.7 1017.94  1031.6 1018.27
#Mann= 3 , 0 , 0
       0      .1       0  519.86    .045       0  542.12     .07       0
Bank Sta=519.86,542.12
XS Rating Curve= 0 ,0
Exp/Cntr=0.3,0.1

Type RM Length L Ch R = 1 ,15741.4 ,411.5,442,471.1
XS GIS Cut Line= 4
     1822378.505      407633.542     1822035.623      407698.646
     1821686.231      407859.237     1821399.773      407776.771
#Sta/Elev= 30
       0 1038.41    59.8 1032.81   119.7 1022.19   159.6  1010.1   169.5  1006.3
   189.5  995.41   199.4  991.22   219.4  985.45   279.2  980.56   309.1  975.62
     339  972.38     349  972.11   368.7   975.2   378.6  975.26   398.3  972.96
   437.8  971.92   457.5  968.12   477.2  961.36     487  960.34   496.9  960.78
   536.3  967.43   556.1  968.02   595.5  972.59   862.7  980.55   872.6  982.23
   902.5  993.98   932.3 1003.81   962.1 1016.52   991.9 1018.54  1031.6 1018.25
#Mann= 3 , 0 , 0
       0      .1       0   477.2    .045       0   496.9     .07       0
Bank Sta=477.2,496.9
XS Rating Curve= 0 ,0
Exp/Cntr=0.3,0.1

Type RM Length L Ch R = 1 ,15299.4 ,389.3,401.4,413.7
XS GIS Cut Line= 4
     1822498.601      407728.449     1822326.726      407540.949
     1822092.351      407348.241     1821628.809      406999.283
#Sta/Elev= 30
       0 1067.91      88 1064.44    97.8 1061.52   127.2 1044.53   176.1 1029.36
   205.4 1016.91     225  1003.7   234.8  999.62   264.1  998.67   313.1  973.27
   322.9  971.03   479.5  966.29   499.1  958.75   505.1  958.41   508.8   958.2
   520.1  959.52   538.2  962.78   646.3   969.7   695.5  994.94   754.5 1013.48
   823.3 1041.84   862.6 1047.25   882.3 1037.66   892.1 1036.87     902 1043.21
   911.8 1054.06   921.6 1059.83  1029.8  1098.1  1049.5 1103.48    1138 1115.46
#Mann= 3 , 0 , 0
       0      .1       0   505.1    .045       0   520.1      .1       0
Bank Sta=505.1,520.1
XS Rating Curve= 0 ,0
Exp/Cntr=0.3,0.1

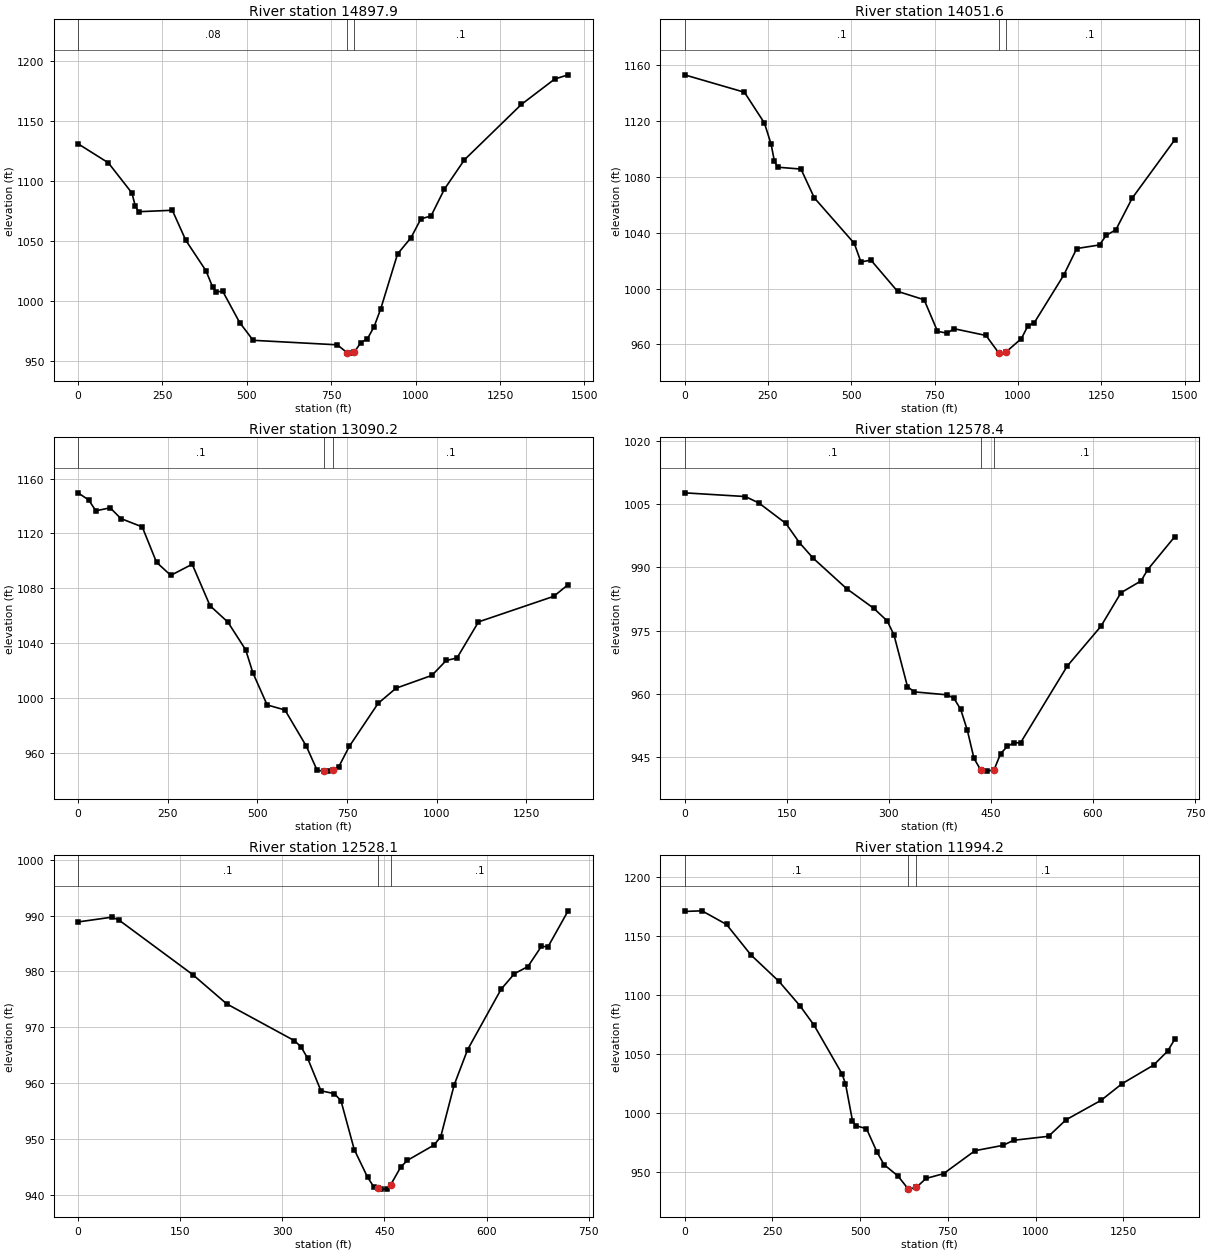
Type RM Length L Ch R = 1 ,14897.9 ,828.8,846.3,863.6
XS GIS Cut Line= 3
     1822719.903      407884.972     1822436.505      407149.695
     1822212.019      406524.919
#Sta/Elev= 30
       0 1130.88    89.8 1114.97   159.6 1089.83   169.6  1078.9   179.5 1074.21
   279.3 1075.41   319.2 1050.38     379 1024.95     399 1011.18     409 1007.53
   428.9 1007.68   478.8  981.77   518.7  966.95     768  963.19  796.61  956.73
   807.8  956.26   817.7   956.8   837.5  964.95   857.4  968.26   877.2  978.41
     897  993.46   946.5 1038.95   986.2 1052.49  1015.9 1068.31  1045.6  1070.6
  1085.3 1092.98  1144.7 1117.52  1313.2 1163.65  1412.2 1184.88  1451.9 1188.38
#Mann= 3 , 0 , 0
       0     .08       0  796.61    .045       0   817.7      .1       0
Bank Sta=796.61,817.7
XS Rating Curve= 0 ,0
Exp/Cntr=0.3,0.1

Type RM Length L Ch R = 1 ,14051.6 ,957.6,961.4,965.3
XS GIS Cut Line= 4
     1822970.953      407883.108     1823186.101      407134.699
     1823295.476      406887.304     1823501.205      406520.116
#Sta/Elev= 30
       0  1153.3   179.7 1140.82   239.6 1118.76   259.6 1103.75   269.6 1091.46
   279.5 1087.08   349.4 1085.74   389.4 1065.08   509.2 1032.49   529.1 1019.16
   559.1  1020.5     639  998.11   718.8  992.06   758.8  969.46   788.4  968.05
   807.7  971.34   904.3  966.46  941.85  954.18     943   953.8  963.68  954.45
  1010.6  964.26  1029.9   973.3  1049.2   975.6  1137.3 1009.63  1176.5 1028.79
    1245 1031.35  1264.6  1038.2  1293.9  1042.2  1342.9  1064.9  1470.1 1106.55
#Mann= 3 , 0 , 0
       0      .1       0  941.85    .045       0  963.68      .1       0
Bank Sta=941.85,963.68
XS Rating Curve= 0 ,0
Exp/Cntr=0.3,0.1

Type RM Length L Ch R = 1 ,13090.2 ,507.9,511.8,515.7
XS GIS Cut Line= 3
      1823440.66       408280.61     1823786.926      407746.389
     1824179.566      407131.136
#Sta/Elev= 30
       0  1149.6    29.8 1144.35    49.7 1136.47    89.5 1138.67   119.4 1130.84
     179 1124.73   218.8 1098.92   258.6 1089.38   318.3  1097.5     368 1067.23
   417.8 1055.25   467.5 1035.02   487.4 1018.32   527.2  994.85   576.9  991.15
   636.6  964.69   666.6  947.15   686.6  946.57   696.6  946.54  710.72  947.14
   726.6  949.56   756.6  964.71   836.6  995.96   886.6 1007.04   986.6  1016.4
  1026.6 1027.28  1056.6 1029.08  1116.5 1055.42  1326.5 1074.09  1366.5 1082.64
#Mann= 3 , 0 , 0
       0      .1       0   686.6    .045       0  710.72      .1       0
Bank Sta=686.6,710.72
XS Rating Curve= 0 ,0
Exp/Cntr=0.3,0.1

Type RM Length L Ch R = 1 ,12578.4 ,50.3,50.3,50.3
XS GIS Cut Line= 4
      1823973.21      408380.099     1824138.141      408097.113
     1824270.085      407953.015     1824398.557       407803.71
#Sta/Elev= 30
       0 1007.66    89.3 1006.78   109.2 1005.26   148.9 1000.41   168.7  995.88
   188.6  992.24   238.2  984.96   277.9  980.32   297.8  977.32   307.7     974
   327.5  961.78   337.3  960.53   386.2  959.82   395.9  958.98   405.7  956.38
   415.5  951.39   425.2  944.78     435  942.07   444.8  941.76   454.7  942.07
   464.3   945.9   474.1   947.6   483.8  948.47   493.6  948.47   562.3  966.66
   611.6  976.04   641.1     984   670.6   986.8   680.5   989.5   719.9  997.23
#Mann= 3 , 0 , 0
       0      .1       0     435    .045       0   454.7      .1       0
Bank Sta=435,454.7
XS Rating Curve= 0 ,0
Exp/Cntr=0.3,0.1

Type RM Length L Ch R = 1 ,12528.1 ,553.4,533.9,514.4
XS GIS Cut Line= 4
     1824002.724      408421.765     1824167.655      408138.779
     1824299.599      407994.682     1824428.071      407845.377
#Sta/Elev= 30
       0  988.87    49.6  989.72    59.6  989.25   168.7  979.42   218.4   974.2
   317.6  967.63   327.5  966.53   337.3  964.45   356.8  958.64   376.4  958.14
   386.2  956.87   405.7  948.13   425.2  943.19     435  941.34  440.04  941.18
   444.8  941.04   454.5  941.06   459.1  941.79   474.1  945.01   483.8  946.19
   522.9  948.93   532.8  950.44   552.5   959.7   572.2     966   621.4  976.82
   641.1  979.62   660.8  980.88   680.5  984.48   690.4  984.44   719.9  990.86
#Mann= 3 , 0 , 0
       0      .1       0  440.04    .045       0   459.1      .1       0
Bank Sta=440.04,459.1
XS Rating Curve= 0 ,0
Exp/Cntr=0.3,0.1

Type RM Length L Ch R = 1 ,11994.2 ,1080,1067,1053.5
XS GIS Cut Line= 3
     1824780.233      408945.588      1824709.26      408331.829
     1824623.297      407558.889
#Sta/Elev= 30
       0 1170.99    49.8 1171.52   119.6 1159.98   189.3 1134.08   269.1 1111.66
   328.9 1090.96   368.7 1074.64   448.4 1033.36   458.4 1024.96   478.3  993.53
   488.3  989.27   518.2  986.84   548.1  967.04     568   956.4   607.9  946.69
  636.43  935.91   637.8  935.57     660  936.98   687.6  944.63   737.5  948.64
   827.2  968.16     907  972.68   936.9  976.96  1036.6  980.36  1086.5  994.37
  1186.2 1010.86    1246 1024.96  1335.7 1040.72  1375.6 1052.52  1395.6 1062.47
#Mann= 3 , 0 , 0
       0      .1       0  636.43    .045       0     660      .1       0
Bank Sta=636.43,660
XS Rating Curve= 0 ,0
Exp/Cntr=0.3,0.1