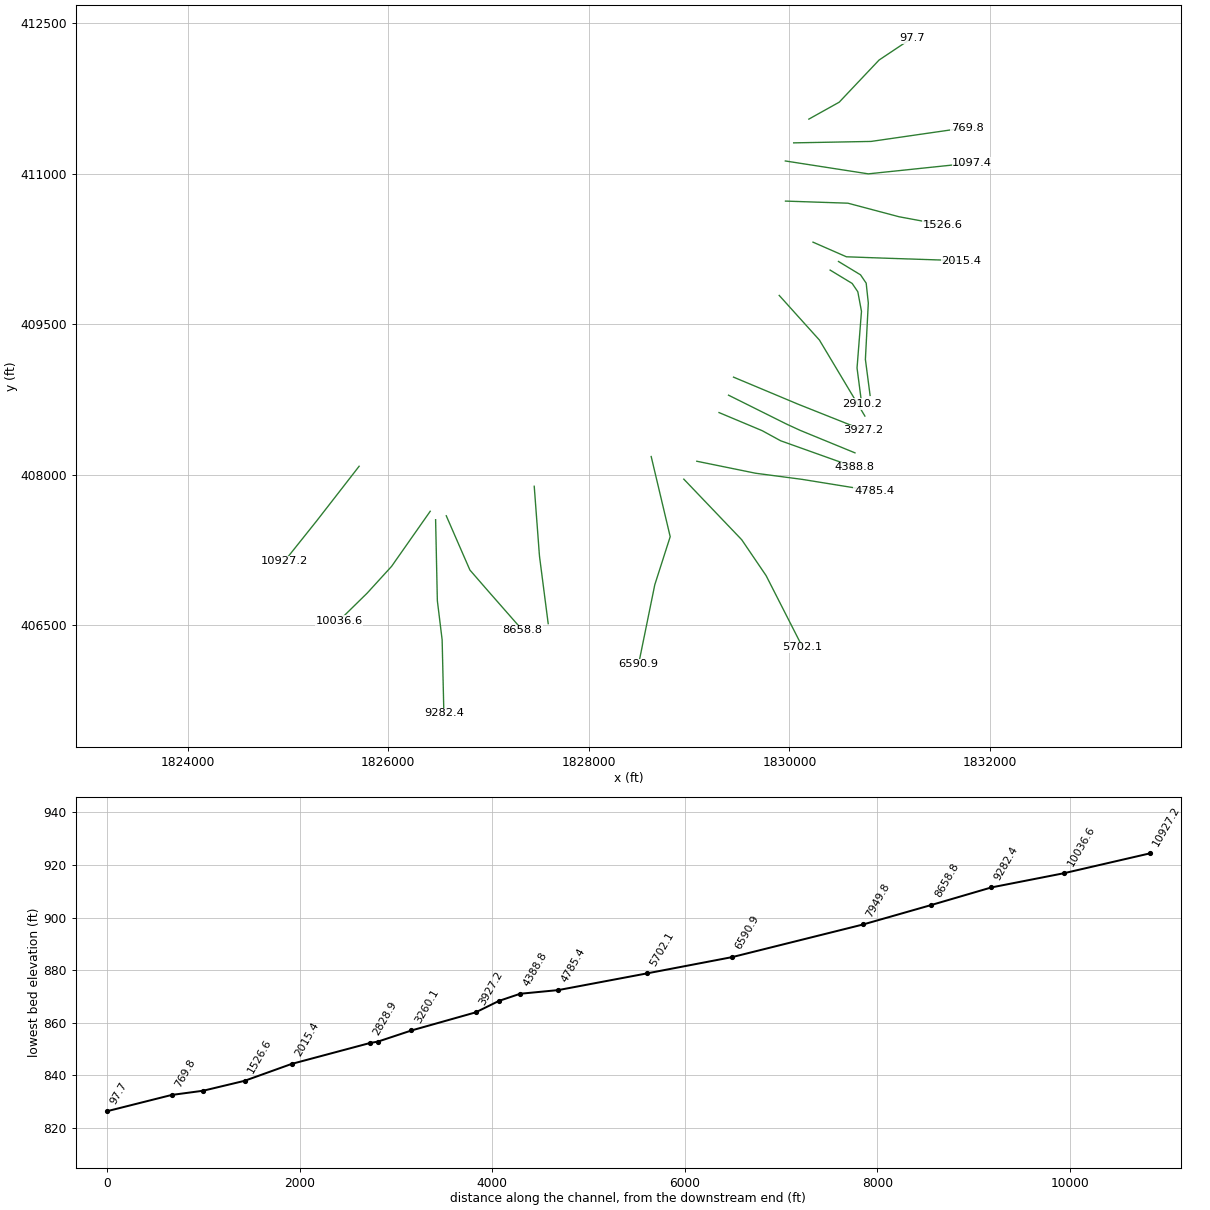
HEC-RAS study DentsRun.prj: DentsRun

--- DentsRun.g01 (geometry) --- (continued)

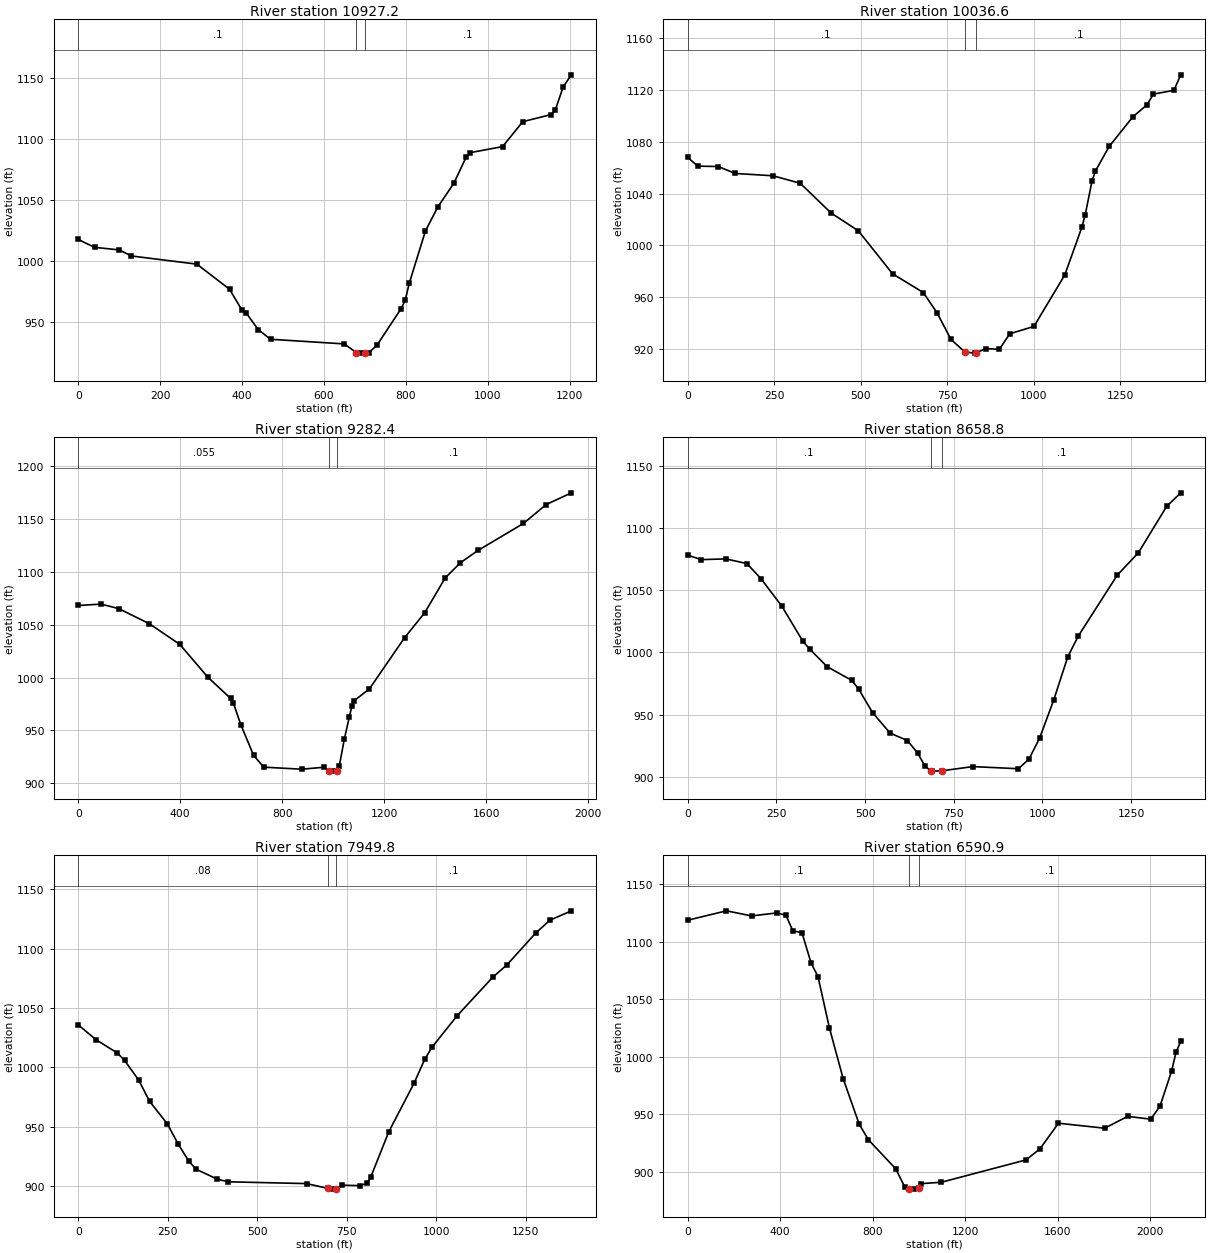
Type RM Length L Ch R = 1 ,10927.2 ,892,890.6,890.2
XS GIS Cut Line= 3
     1825708.632      408083.494     1825285.736      407539.191
     1824964.443      407137.014
#Sta/Elev= 30
       0 1017.51      40 1011.05    99.9 1008.96   129.9 1003.99   289.7  997.28
   369.6  976.66   399.6  959.68   409.6  957.52   439.5  943.61   469.5  935.74
   649.3  931.94   679.3  924.73   689.3  924.39   699.2   924.4   709.1  924.75
   728.9  930.67   788.3  960.87   798.2  967.62   808.1  981.64   847.7 1024.54
   877.4 1043.93     917 1063.58   946.7 1084.74   956.6 1088.61  1035.8 1093.56
  1085.2    1114  1154.5 1119.84  1164.4 1123.41  1184.2 1142.77    1204 1152.38
#Mann= 3 , 0 , 0
       0      .1       0   679.3    .045       0   699.2      .1       0
Bank Sta=679.3,699.2
XS Rating Curve= 0 ,0
Exp/Cntr=0.3,0.1

Type RM Length L Ch R = 1 ,10036.6 ,735,754.2,772.7
XS GIS Cut Line= 4
     1826417.568       407634.41     1826032.151      407084.931
     1825789.964      406819.306     1825508.714      406543.264
#Sta/Elev= 30
       0 1068.18    29.6  1061.3    88.8 1060.99   138.2 1055.63   246.8 1053.85
   325.7 1048.04   414.6 1025.13   493.5 1011.32   592.2  978.15   681.2  963.63
   721.1  947.84     761  927.45     801  917.77     830  916.86  833.23  916.96
   860.9  920.35   900.8  919.84   930.8  931.78  1000.7  937.51  1089.8   977.3
    1139 1014.05  1148.9 1023.92  1168.6 1050.06  1178.4 1057.59  1217.8 1076.47
  1286.8 1099.52  1326.2 1108.37  1345.9 1116.91    1405 1119.88  1424.7 1131.82
#Mann= 3 , 0 , 0
       0      .1       0     801    .045       0  833.23      .1       0
Bank Sta=801,833.23
XS Rating Curve= 0 ,0
Exp/Cntr=0.3,0.1

Type RM Length L Ch R = 1 ,9282.4  ,612.5,623.6,630.6
XS GIS Cut Line= 4
     1826471.387      407550.209     1826488.748      406742.917
     1826536.492      406352.292     1826553.853      405618.785
#Sta/Elev= 30
       0 1068.26    89.7 1069.58   159.5 1065.25   279.1 1051.01   398.8 1031.38
   508.4  1000.4   598.1  980.23   608.1  976.32     638   955.3   687.8  926.49
   727.7  915.21   876.4  913.28   964.9  915.14   984.6  911.77   994.4  911.45
 1015.21  911.88  1023.9  915.94  1043.6  941.51  1063.3  962.49  1073.1  972.64
    1083  978.23    1142  989.24  1280.3 1037.79  1359.6 1061.54    1439 1094.18
  1498.5 1108.63  1567.9 1120.33  1746.3 1145.94  1835.6 1163.84  1934.7 1174.93
#Mann= 3 , 0 , 0
       0    .055       0   984.6    .045       0 1015.21      .1       0
Bank Sta=984.6,1015.21
XS Rating Curve= 0 ,0
Exp/Cntr=0.3,0.1

Type RM Length L Ch R = 1 ,8658.8  ,721.3,709,701.4
XS GIS Cut Line= 4
     1826577.526      407589.724     1826813.401      407048.473
     1826985.276      406850.556     1827339.443       406446.91
#Sta/Elev= 30
       0 1078.11    39.4 1074.52   108.2 1075.12   167.3 1071.36   206.6 1059.36
   265.7 1037.16   324.7 1009.14   344.4 1002.64   393.6  988.54   462.5  977.65
   482.2   970.6   521.5  951.66   570.7   935.3   619.5  929.31   648.7  919.13
   668.1   909.2  684.61  905.01   687.5  904.77   716.6  905.03     804  908.41
   932.1   906.7   961.9   914.4   991.8  931.22  1031.5  961.72  1071.3   996.6
  1101.2 1013.34  1210.5 1062.03  1270.2 1080.07  1349.8 1117.26  1389.5 1128.14
#Mann= 3 , 0 , 0
       0      .1       0  684.61    .045       0   716.6      .1       0
Bank Sta=684.61,716.6
XS Rating Curve= 0 ,0
Exp/Cntr=0.3,0.1

Type RM Length L Ch R = 1 ,7949.8  ,1367.7,1358.9,1349
XS GIS Cut Line= 3
     1827454.925      407883.785     1827507.222      407188.012
     1827594.242      406513.616
#Sta/Elev= 30
       0 1035.76    49.8 1023.24   109.6 1011.95   129.6 1005.76   169.4  988.98
   199.4  971.29   249.2  952.25   279.1  935.46     309  920.87   328.9  914.17
   388.7  905.71   418.6  903.53   637.9  902.02     697  898.01   707.7  897.36
  719.01   897.6   737.7  900.68   787.7  900.28   807.7  902.53   817.7  907.96
   867.7  945.79   937.7  986.36   967.7 1006.56   987.7 1016.71  1057.7 1043.15
  1157.7  1075.8  1197.7 1086.36  1277.7 1113.02  1317.7 1123.92  1377.7 1131.79
#Mann= 3 , 0 , 0
       0     .08       0     697    .045       0  719.01      .1       0
Bank Sta=697,719.01
XS Rating Curve= 0 ,0
Exp/Cntr=0.3,0.1

Type RM Length L Ch R = 1 ,6590.9  ,868,888.8,909.5
XS GIS Cut Line= 4
     1828621.561      408180.417     1828811.057      407380.967
     1828657.412        406901.8     1828495.953      406110.134
#Sta/Elev= 30
       0 1118.76   168.3 1126.96   277.2 1122.53     386 1125.13   425.6 1123.12
   455.4 1109.55   494.9 1107.99   534.5 1081.44   564.2 1069.77   613.7 1025.01
   673.1     981   742.4  941.41     782  927.94   900.5  902.55     940   886.6
   959.7  885.44   979.5  884.96   999.2  886.31  1009.1  889.71  1097.9  890.95
  1464.4  910.41  1524.3  920.08  1604.1  942.27  1803.6  937.93  1903.3  948.25
  2003.1  945.77    2043   957.1  2092.9  987.43  2112.8 1004.22  2132.8 1013.41
#Mann= 3 , 0 , 0
       0      .1       0   959.7    .045       0   999.2      .1       0
Bank Sta=959.7,999.2
XS Rating Curve= 0 ,0
Exp/Cntr=0.3,0.1

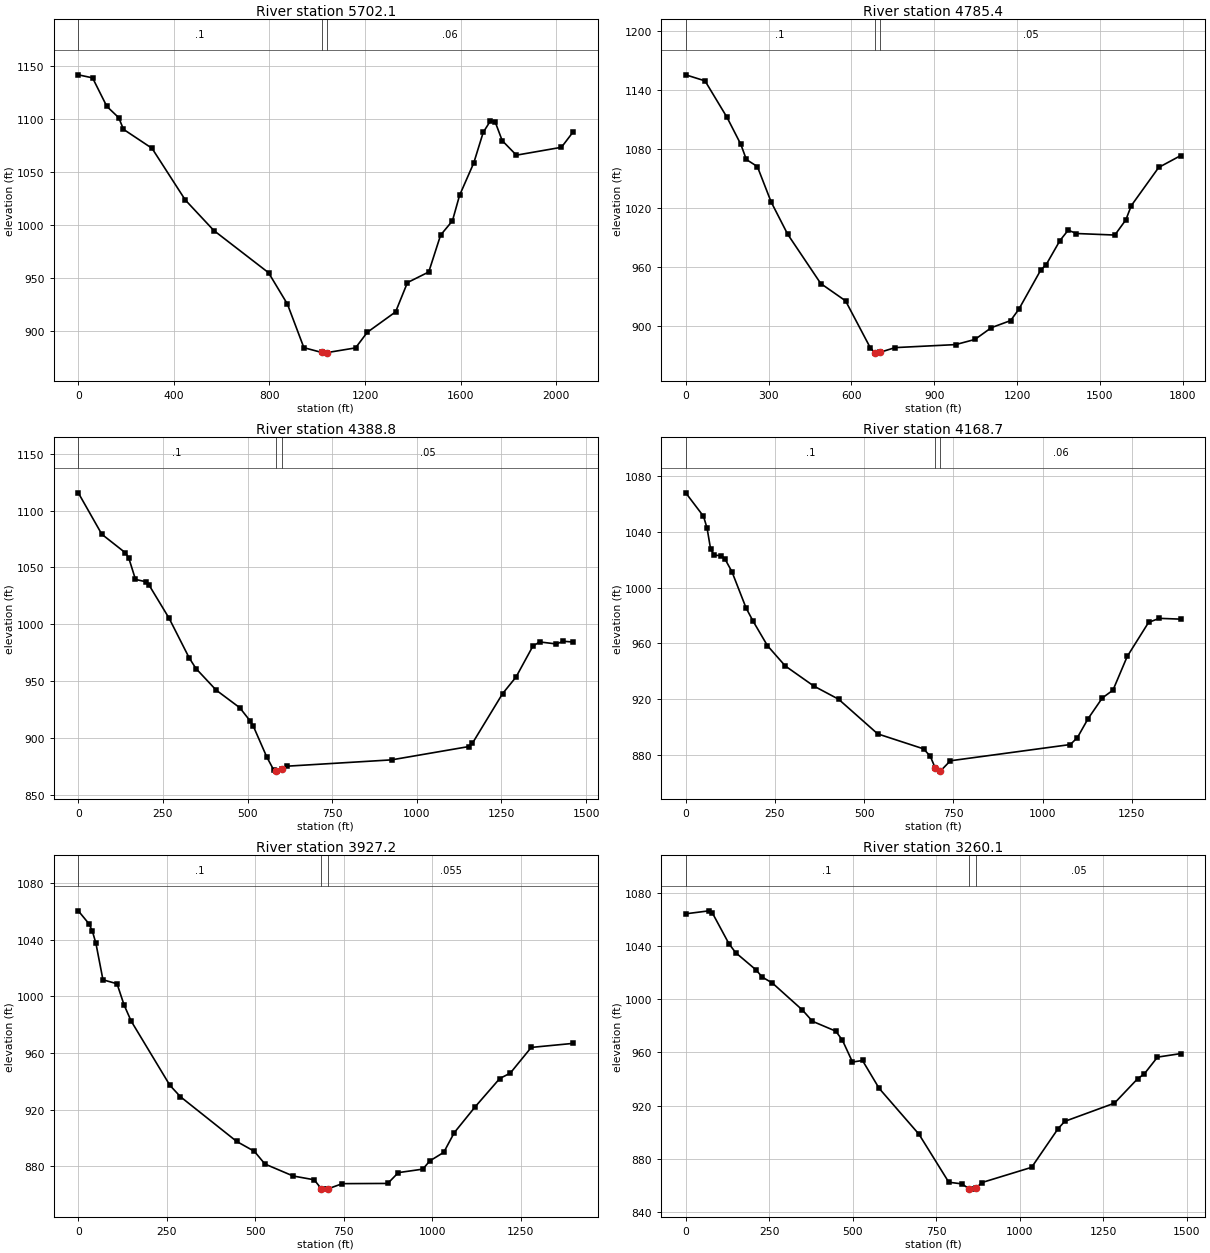
Type RM Length L Ch R = 1 ,5702.1  ,897.5,916.8,936.1
XS GIS Cut Line= 4
     1828946.837      407954.867     1829524.339      407350.556
     1829767.394      406992.917     1830131.978      406277.639
#Sta/Elev= 30
       0 1141.25    59.7 1138.39   119.4 1111.51   169.2 1100.82   189.1 1089.84
   308.5 1071.94   447.8 1023.18   567.2   994.4   796.1  954.59   875.2  924.95
     944  883.88  1019.4  879.34  1032.4  878.74  1042.3  879.29  1160.2  883.68
  1209.3  898.39  1327.8  917.65  1377.3  945.28  1466.5  955.28  1516.1  990.07
  1565.6 1003.53  1595.4 1027.53  1654.8 1058.11  1694.5 1087.01  1724.2 1097.69
    1744  1097.1  1773.8 1079.21  1833.2 1065.47  2021.6 1072.88  2071.1 1087.51
#Mann= 3 , 0 , 0
       0      .1       0  1019.4    .045       0  1042.3     .06       0
Bank Sta=1019.4,1042.3
XS Rating Curve= 0 ,0
Exp/Cntr=0.3,0.1

Type RM Length L Ch R = 1 ,4785.4  ,404.8,396.6,388.3
XS GIS Cut Line= 4
     1829076.386      408133.394     1829663.228       408013.75
     1830127.759      407952.533     1830843.783      407836.667
#Sta/Elev= 30
       0 1155.63    69.9 1149.48   149.7 1112.28   199.6 1084.88   219.6 1069.47
   259.5 1062.29   309.4 1026.24   369.3   993.4   489.1  943.24     579  925.62
   668.7  877.82  684.72  872.76   688.6  872.42   704.9  873.36   758.4  878.03
   977.7   881.1  1047.5  886.34  1107.2  898.34  1176.8  905.53  1206.6  917.06
  1286.1  957.03  1305.9  962.59  1355.6  987.01  1385.4  997.54  1415.2  994.15
  1554.3  992.58  1594.1 1007.98    1614 1022.53  1713.3  1061.4  1792.8 1073.42
#Mann= 3 , 0 , 0
       0      .1       0  684.72    .045       0   704.9     .05       0
Bank Sta=684.72,704.9
XS Rating Curve= 0 ,0
Exp/Cntr=0.3,0.1

Type RM Length L Ch R = 1 ,4388.8  ,218,220.1,222.4
XS GIS Cut Line= 4
     1829298.037      408618.814     1829728.592      408438.259
      1829912.62      408337.564     1830652.203      408073.675
#Sta/Elev= 30
       0 1115.54    69.5 1079.14   139.1 1062.85     149 1058.36   168.9 1039.47
   198.7 1037.46   208.6 1034.69   268.2 1005.34   327.8  970.38   347.7  961.12
   407.3  942.18   476.9  926.74   506.8  915.44   516.8  910.65   556.8   883.4
   576.8  872.25  582.56  871.49   586.8  871.02   601.1   872.6   616.7  875.37
   925.2  880.91  1153.8  892.62  1163.7  895.31  1253.2   939.1  1292.9  953.67
  1342.6  980.79  1362.5  984.54  1412.2  982.74  1432.1  985.12  1461.9  984.45
#Mann= 3 , 0 , 0
       0      .1       0  582.56    .045       0   601.1     .05       0
Bank Sta=582.56,601.1
XS Rating Curve= 0 ,0
Exp/Cntr=0.3,0.1

Type RM Length L Ch R = 1 ,4168.7  ,241.6,241.5,241.9
XS GIS Cut Line= 4
     1829393.062      408792.175     1829972.489      408503.547
     1830109.207      408440.613     1830653.912      408217.088
#Sta/Elev= 30
       0 1067.98    49.8 1051.14    59.8 1042.67    69.7 1027.65    79.7 1023.26
    99.6 1022.86   109.6 1020.67   129.5 1011.36   169.3  985.22   189.2  975.69
   229.1  958.26   278.8  943.78   358.5   929.4   428.2   919.9   537.8  895.03
   666.2  884.29     685  879.05   698.7  870.74   713.2   868.3   713.7   868.4
   741.4  875.73  1077.3  887.37  1097.2  892.33  1127.2  905.93  1167.1   920.8
    1197  926.42  1236.9  950.59  1296.8  975.04  1326.8  977.92  1386.6  977.35
#Mann= 3 , 0 , 0
       0      .1       0   698.7    .045       0   713.7     .06       0
Bank Sta=698.7,713.7
XS Rating Curve= 0 ,0
Exp/Cntr=0.3,0.1

Type RM Length L Ch R = 1 ,3927.2  ,679.6,667.1,653.1
XS GIS Cut Line= 3
      1829442.66      408972.221      1830085.17         408703.
     1830737.552       408443.55
#Sta/Elev= 30
       0 1060.46    29.9 1051.38    39.8 1046.12    49.8 1037.51    69.7 1011.77
   109.5 1008.96   129.4     994   149.3  982.66   258.8  937.28   288.6  929.21
   447.8  897.59   497.6  890.64   527.4  881.68   607.1  873.22   666.8  870.54
   686.7  864.17   696.6  863.95   706.5  864.23   746.1  867.82   874.6  867.97
   904.3   875.6   973.5  878.06   993.3  883.85  1032.8  889.93  1062.5  903.82
  1121.8  922.15  1191.1  942.06  1220.7  945.84    1280  964.01  1398.7  966.87
#Mann= 3 , 0 , 0
       0      .1       0   686.7    .045       0   706.5    .055       0
Bank Sta=686.7,706.5
XS Rating Curve= 0 ,0
Exp/Cntr=0.3,0.1

Type RM Length L Ch R = 1 ,3260.1  ,364.6,349.9,334.6
XS GIS Cut Line= 3
     1829898.471      409787.188     1830299.512      409341.875
     1830752.637      408584.063
#Sta/Elev= 30
       0  1064.4    69.9 1066.64    79.9    1065   129.8 1041.69   149.8 1035.08
   209.8 1022.33   229.7 1016.66   259.7 1012.22   349.6  991.91   379.5  983.47
   449.5  976.01   469.4  969.12   499.4  952.77   529.4  953.93   579.3  932.92
   698.5   898.4   787.8  862.26   827.5     861   847.3  857.48   857.2  857.06
   870.2  858.08     887  862.01  1035.8  873.47  1115.2  902.61    1135  908.08
  1283.8  921.79  1353.3  940.18  1373.1  943.78  1412.8  956.47  1482.2  959.12
#Mann= 3 , 0 , 0
       0      .1       0   847.3    .045       0   870.2     .05       0
Bank Sta=847.3,870.2
XS Rating Curve= 0 ,0
Exp/Cntr=0.3,0.1

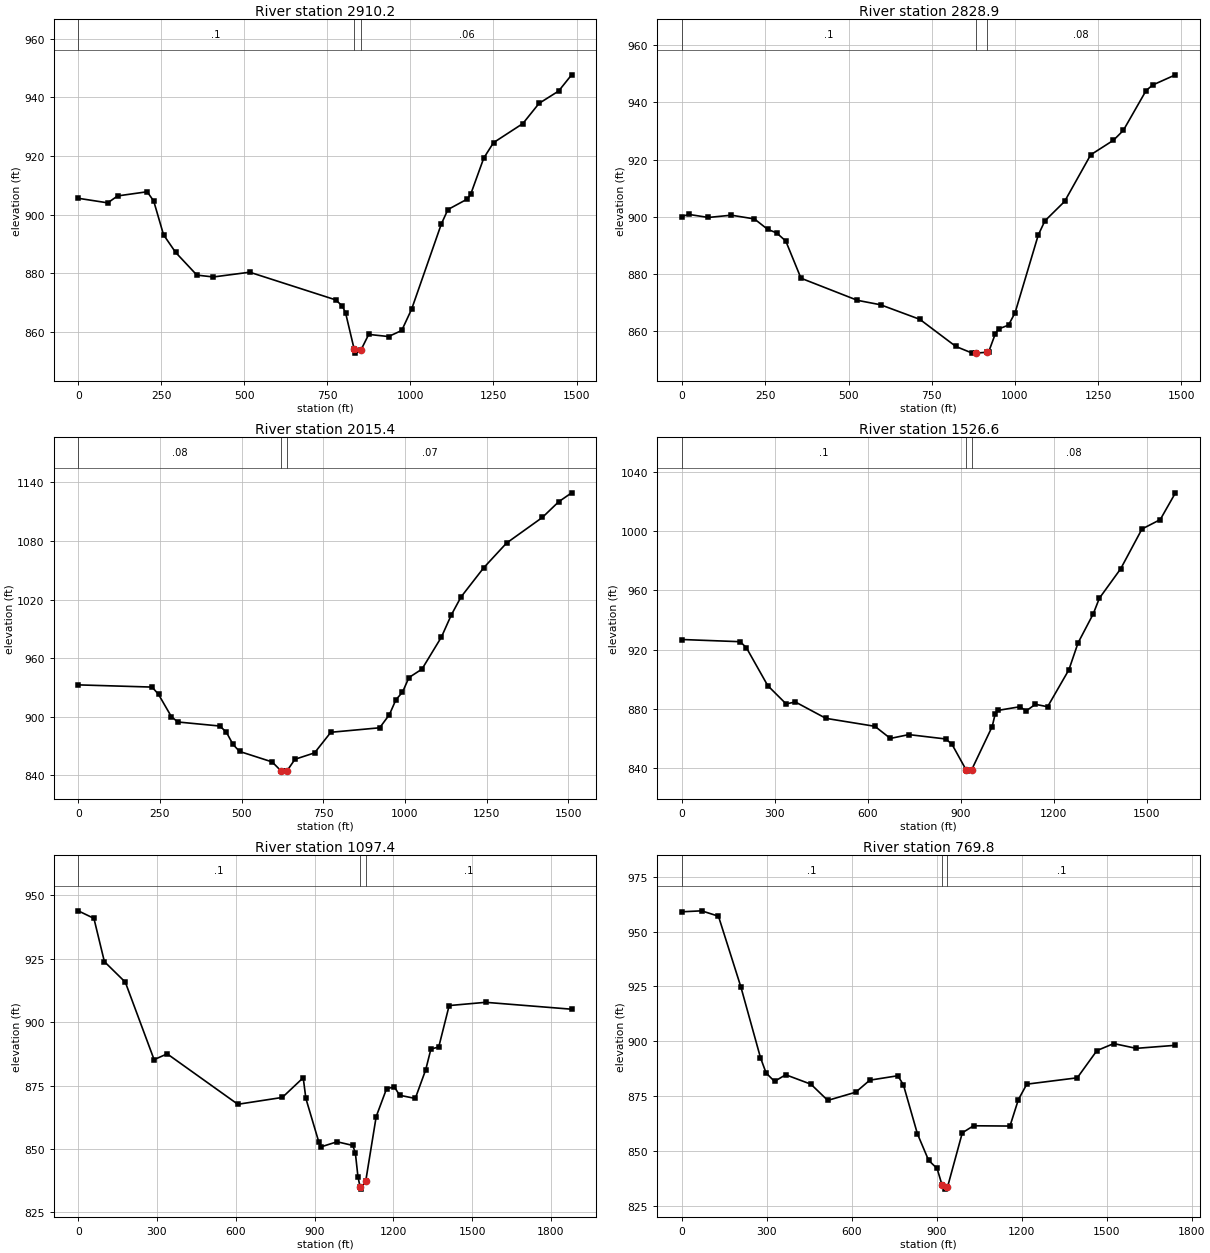
Type RM Length L Ch R = 1 ,2910.2  ,124.7,81.3,79.4
XS GIS Cut Line= 6
     1830406.283      410039.792     1830625.975      409906.688
     1830682.325      409823.646     1830718.783      409628.334
     1830674.512       409063.23     1830721.387      408703.855
#Sta/Elev= 30
       0  905.57    88.9  904.01   118.6  906.37   207.5  907.79   227.2  904.65
   256.9  893.12   293.4  887.11   357.2  879.39   406.9  878.76   516.2  880.38
   774.9  870.96   794.8   868.9   804.8  866.54   830.2  854.38   834.6  852.81
  851.22   853.9   874.5  859.19   934.2  858.46   973.9  860.54  1003.7  867.81
  1093.1  896.82  1112.9  901.73  1171.8  905.34  1181.6  906.98  1220.8  919.27
  1250.2  924.53  1338.4  931.02  1387.3  937.91  1446.1   942.1  1485.3  947.63
#Mann= 3 , 0 , 0
       0      .1       0   830.2    .045       0  851.22     .06       0
Bank Sta=830.2,851.22
XS Rating Curve= 0 ,0
Exp/Cntr=0.3,0.1

Type RM Length L Ch R = 1 ,2828.9  ,732.6,813.5,853.4
XS GIS Cut Line= 6
     1830489.617       410125.73     1830709.308      409992.626
     1830765.658      409909.584     1830786.897      409711.117
     1830757.846      409149.167     1830804.721      408789.792
#Sta/Elev= 30
       0  900.08    19.8  900.83      79  899.76   148.2  900.55   217.4  899.24
   256.9  895.62   284.2  894.34   311.6   891.5   357.2   878.5   526.9  870.76
   596.2  869.21   714.2  864.11   822.4  854.62   871.6  852.29   881.4   852.3
  916.31  852.59   920.9  852.73   940.7     859   950.7  860.74   980.5  862.09
  1000.3  866.45  1069.9  893.62  1089.7  898.55  1148.9  905.35  1227.3  921.67
  1295.8  926.78  1325.2  930.19  1393.8  944.17  1413.4  946.09  1481.9  949.66
#Mann= 3 , 0 , 0
       0      .1       0   881.4    .045       0  916.31     .08       0
Bank Sta=881.4,916.31
XS Rating Curve= 0 ,0
Exp/Cntr=0.3,0.1

Type RM Length L Ch R = 1 ,2015.4  ,493.8,488.9,483.9
XS GIS Cut Line= 4
     1830235.276      410318.438      1830568.61      410172.605
     1830927.985      410159.584     1831714.443      410133.542
#Sta/Elev= 30
       0  932.62   226.2  930.36   245.8  922.88   285.2  900.08   304.8  894.64
   433.8  890.49   453.7  884.06   473.7  871.74   493.7  864.52   593.6  853.75
   620.9  844.56   623.6  844.34   639.4   844.8   663.5  856.48   723.4  863.02
   773.2   884.1   922.7   888.7   952.5  902.14   972.5  917.46   992.4  925.05
  1012.3  940.11  1052.2  948.76  1111.9  981.67  1141.8 1004.08  1171.7 1022.59
  1241.4 1052.58  1311.1 1077.77  1420.7 1103.99  1470.5    1120  1510.3 1129.19
#Mann= 3 , 0 , 0
       0     .08       0   620.9    .045       0   639.4     .07       0
Bank Sta=620.9,639.4
XS Rating Curve= 0 ,0
Exp/Cntr=0.3,0.1

Type RM Length L Ch R = 1 ,1526.6  ,421,429.2,437.4
XS GIS Cut Line= 4
     1829960.971      410728.015     1830583.367      410707.182
     1831093.783      410571.765     1831528.679      410491.036
#Sta/Elev= 30
       0  926.75   187.8  925.27   207.6  921.26   276.8  895.61   336.1  883.27
   365.7   884.6   464.6  873.53   622.7  868.16   672.6  859.98   732.3  862.56
   851.9   859.6   871.8  855.94   917.2  838.76   921.6  837.91  934.78  838.67
  1001.4  868.01  1011.3  876.74  1021.3  878.94    1091  881.38    1111  878.56
  1140.9  883.01  1180.3  881.37  1249.1  906.35  1278.6  924.46  1327.8  944.11
  1347.4   954.6  1416.2  974.48    1485 1001.34    1544 1007.68  1593.1 1025.76
#Mann= 3 , 0 , 0
       0      .1       0   917.2    .045       0  934.78     .08       0
Bank Sta=917.2,934.78
XS Rating Curve= 0 ,0
Exp/Cntr=0.3,0.1

Type RM Length L Ch R = 1 ,1097.4  ,326.7,327.6,328.5
XS GIS Cut Line= 3
     1829959.235      411128.189     1830786.492      410999.717
      1831822.95      411108.224
#Sta/Elev= 30
       0  943.87    59.8   940.9    99.7  923.84   179.4  915.74     289  885.21
   338.9  887.48     608   867.6   777.4   870.3     857  878.07     867  869.93
   916.6  852.64   926.5  850.87     986  852.82  1045.6  851.38  1055.5  848.45
  1065.4  839.11 1073.51  835.02  1075.4  834.15  1095.3  837.48  1134.9  862.74
  1174.6  873.78  1204.4  874.38  1224.2  871.16  1283.8   869.9  1323.5   881.2
  1343.4   889.4  1373.1  890.16  1412.8  906.52  1551.8   907.8  1879.3  905.08
#Mann= 3 , 0 , 0
       0      .1       0 1073.51    .045       0  1095.3      .1       0
Bank Sta=1073.51,1095.3
XS Rating Curve= 0 ,0
Exp/Cntr=0.3,0.1

Type RM Length L Ch R = 1 ,769.8   ,656.9,672,687.2
XS GIS Cut Line= 3
     1830042.568      411308.745     1830814.404      411323.063
     1831775.207      411461.956
#Sta/Elev= 30
       0     959    69.3  959.44   128.7  956.98   207.8  924.75   277.1  892.47
   296.9   885.5   326.6  881.67   366.2  884.69   455.3  880.38   514.6     873
   613.6  876.74   663.1  882.22   762.1  884.24   781.9   880.1   831.4  857.76
     871  845.65   900.8  841.97   918.3  834.43   930.5  832.54  937.56  833.41
   989.9  858.21  1029.5  861.43  1158.3   861.3    1188  873.37  1217.7   880.4
    1396   883.3  1465.4  895.71  1524.8  898.91  1604.1  896.73  1742.8  898.12
#Mann= 3 , 0 , 0
       0      .1       0   918.3    .045       0  937.56      .1       0
Bank Sta=918.3,937.56
XS Rating Curve= 0 ,0
Exp/Cntr=0.3,0.1

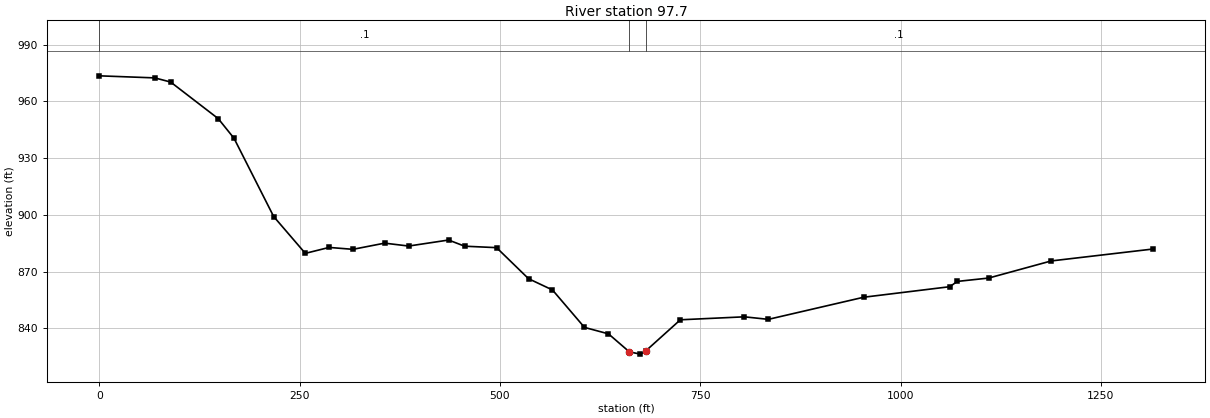
Type RM Length L Ch R = 1 ,97.7    ,99.1,97.7,96.4
XS GIS Cut Line= 4
     1830194.044      411545.724     1830496.387      411714.283
     1830894.033      412134.607     1831218.349      412351.279
#Sta/Elev= 30
       0  973.45    69.2  972.36      89  970.16   148.4  950.82   168.1  940.44
   217.6  899.08   257.1  879.61   286.8  882.75   316.5  881.74   356.1  885.01
   386.1  883.48   435.9  886.66   455.9   883.4   495.8  882.63   535.7  866.22
   565.6  860.26   605.5  840.48   635.5  837.06  661.61  827.52   675.4  826.35
   681.7  827.93   725.2   844.5   805.1  846.07     835  844.73     954  856.42
  1061.3  861.98    1071  864.79    1110  866.56    1188   875.6  1314.8  881.89
#Mann= 3 , 0 , 0
       0      .1       0  661.61    .045       0   681.7      .1       0
Bank Sta=661.61,681.7
XS Rating Curve= 0 ,0
Exp/Cntr=0.3,0.1

Chan Stop Cuts=-1
Use User Specified Reach Order=0
Composite Channel Slope=5